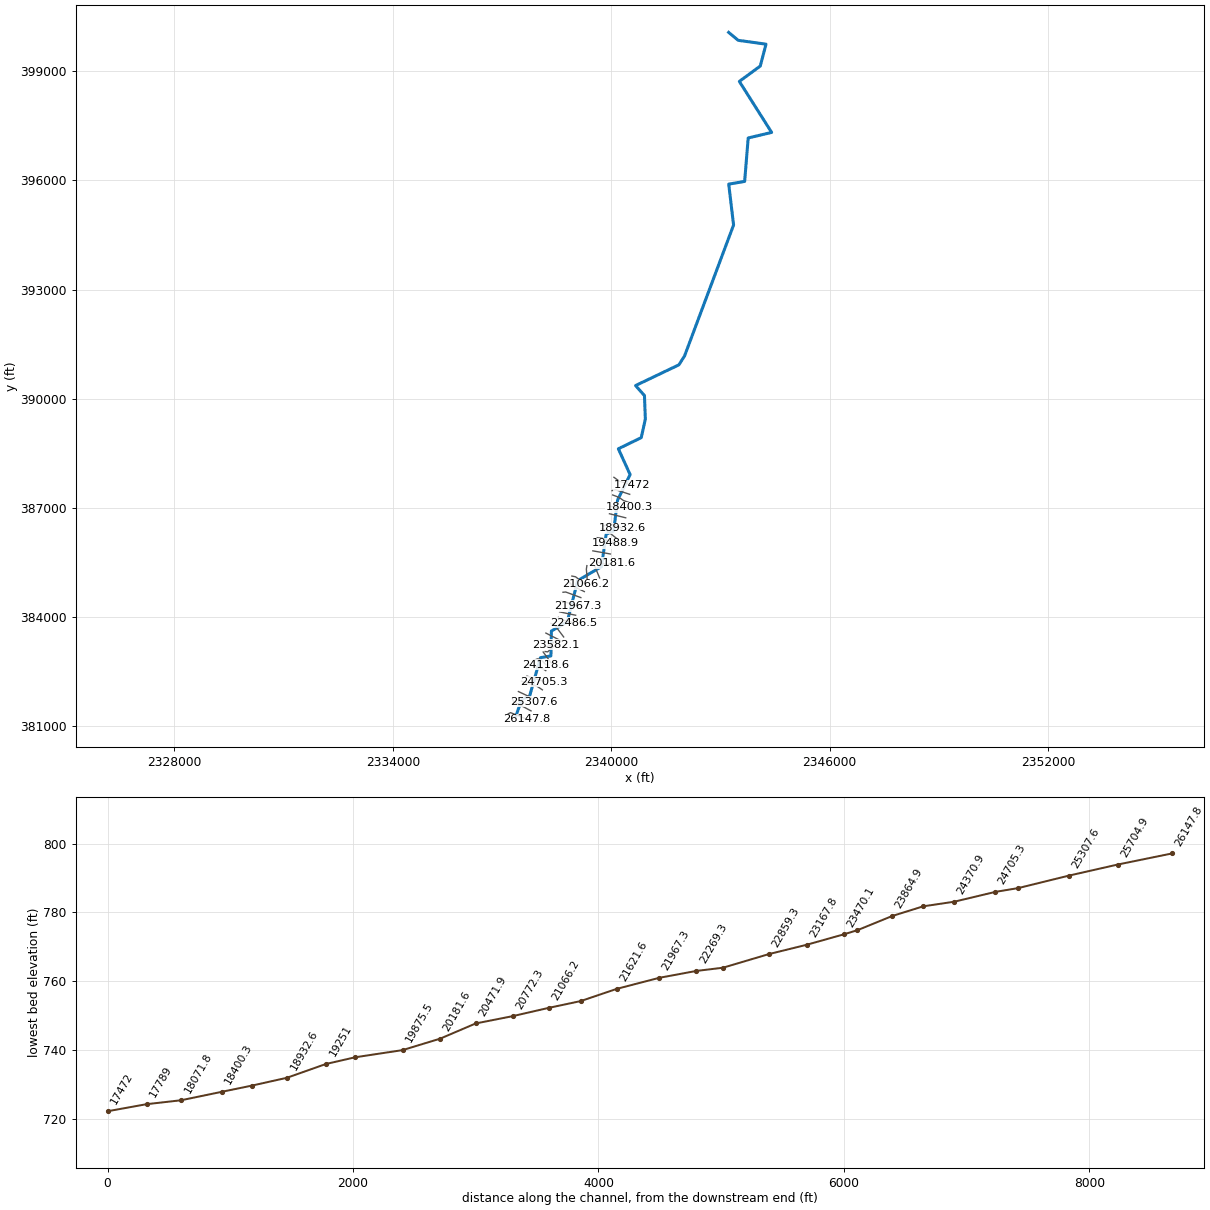
--- MOUNTAINRN.prj (project) ---

Proj Title=MOUNTAINRN
Current Plan=p01
Default Exp/Contr=0,0
English Units
Geom File=g01
Flow File=f01
Plan File=p01
BEGIN DESCRIPTION:
END DESCRIPTION:
DSS Export Rating Curves= 0
DSS Export Rating Curve Sorted= 0
DSS Export Volume Flow Curves= 0
DXF OffsetX= 0
DXF OffsetY= 0
DXF ScaleX= 0
DXF ScaleY= 0

--- MOUNTAINRN.p01 (plan) ---

Plan Title=Floodplain
Program Version=4.00
Geom File=g01
Flow File=f01
K Sum by GR=0
Std Step Tol=0.01
Critical Tol=0.01
Num of Std Step Trials=20
Max Error Tol=0.3
Flow Tol Ratio=0.001
Split Flow NTrial=30
Split Flow Tol=0.02
Split Flow Ratio=0.02
Log Output Level=0
Friction Slope Method=1
Unsteady Friction Slope Method=2
Unsteady Bridges Friction Slope Method=1
Global Log Level=0
CheckData=False
Run HTab=0
Run UNet=0
Run PostProcess=0
UNET Theta=0
UNET Theta Warmup=0
UNET ZTol=0
UNET ZSATol=0
UNET MxIter=0
UNET MaxInSteps=0
UNET DtIC=0
UNET DtMin=0
UNET MaxCRTS=0
UNET WFStab=0
UNET SFStab=0
UNET WFX=0
UNET SFX=0
UNET DSS MLevel=0
UNET DZMax Abort=0
UNET Convert EG Bridges=0
UNET Use Existing IB Tables=0
UNET Froude Limit=0
UNET Froude Power=0
Write IC File=0
Echo Input=False
Echo Output=False
Write Detailed=0

--- MOUNTAINRN.f01 (steady flow) ---

Flow Title=NFF Regression Equation
Program Version=4.00
Number of Profiles=1
Profile Names=P100yr
River Rch & RM=MOUNTAINRN,Main      ,26147.8
514.4392
River Rch & RM=MOUNTAINRN,Main      ,25704.9
537.2139
River Rch & RM=MOUNTAINRN,Main      ,23864.9
585.9144
River Rch & RM=MOUNTAINRN,Main      ,23167.8
669.4061
River Rch & RM=MOUNTAINRN,Main      ,20772.3
725.0361
River Rch & RM=MOUNTAINRN,Main      ,20471.9
835.4880
River Rch & RM=MOUNTAINRN,Main      ,19875.5
901.0056
River Rch & RM=MOUNTAINRN,Main      ,17312.9
954.7054
River Rch & RM=MOUNTAINRN,Main      ,17037.5
1066.490
River Rch & RM=MOUNTAINRN,Main      ,12674.6
1166.564
River Rch & RM=MOUNTAINRN,Main      ,12206.1
1297.345
River Rch & RM=MOUNTAINRN,Main      ,9107.8
1398.739
River Rch & RM=MOUNTAINRN,Main      ,8065.9
1543.329
River Rch & RM=MOUNTAINRN,Main      ,5770.7
1667.651
River Rch & RM=MOUNTAINRN,Main      ,552.7
1832.853
River Rch & RM=MOUNTAINRN,Main      ,142.2
1834.591
Boundary for River Rch & Prof#=MOUNTAINRN,Main      ,1
Up Type=0
Dn Type=3
Dn Slope=0.008811

--- MOUNTAINRN.g01 (geometry) ---

Geom Title=USGS 10m DEM
Program Version=4.10

River Reach=MOUNTAINRN      ,Main
Reach XY= 30
     2337382.605      381287.683     2337540.591      381747.752
     2337757.605      381834.557      2338054.48      382890.113
     2338342.675      382938.724     2338356.563      383622.752
     2338788.855      383867.544     2339077.049      385004.696
     2339731.564      385391.849     2339858.299      386279.002
     2340064.897       386369.28     2340174.272      387219.974
     2340518.022      387919.627     2340195.105       388627.96
     2340823.577      388933.516     2340936.425      389442.196
     2340912.119      390089.766     2340667.327      390364.071
     2341858.299      390933.516     2342012.814      391176.571
     2343360.036      394773.793     2343226.355      395897.058
     2343663.855       395971.71     2343761.077      397164.419
     2344405.175      397317.196     2343518.022      398718.238
     2344092.675      399140.113     2344250.661      399740.807
     2343486.772       399846.71     2343224.619      400064.078

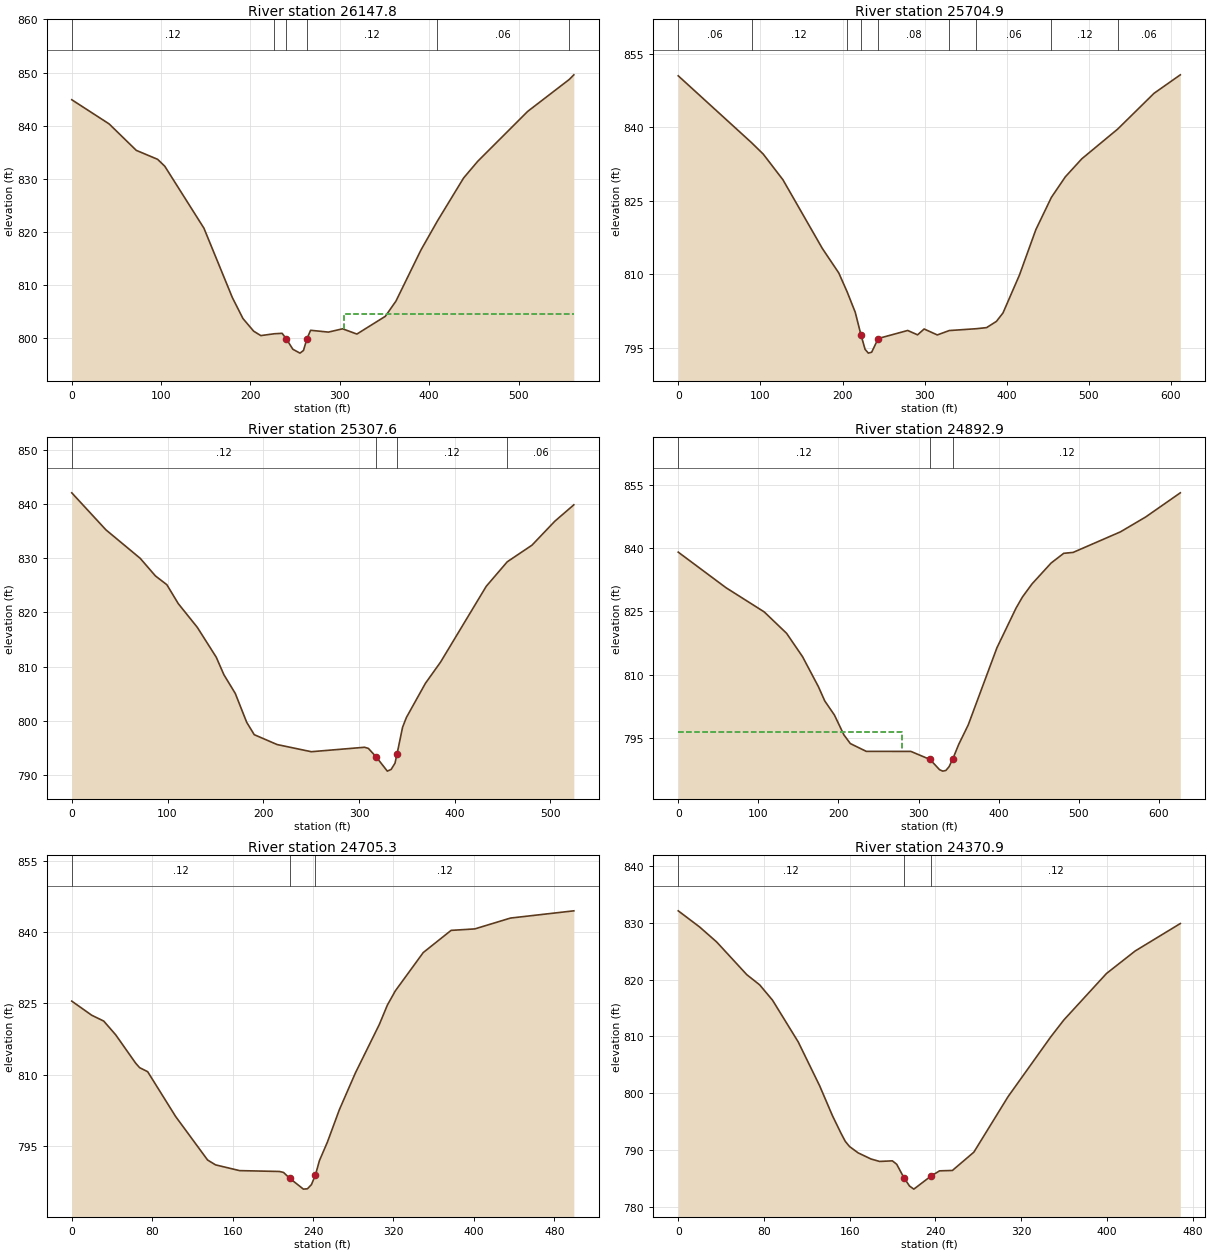
Type RM Length L Ch R = 1 ,26147.8 ,446.8,442.9,423.8
XS GIS Cut Line= 3
     2337170.204       381348.78     2337235.016      381380.618
     2337689.302      381197.738
#Sta/Elev= 30
       0  844.88    41.8  840.33    72.2  835.35    96.1  833.66   104.1  832.36
   147.9   820.7   179.7  807.64   191.6  803.68   203.6   801.3   211.6  800.47
  226.72800.8185   235.4   800.9     240  799.89   247.4   797.9   255.4  797.17
   259.3  797.67   263.3  799.92   267.3  801.47   287.2  801.13   303.1  801.75
   319.1  800.76   350.9   804.1   362.8  806.96   390.7  816.56  409.19822.0422
   438.5  830.14   454.4   833.3   510.2  842.68  556.67848.6844   561.9  849.57
#Mann= 6 ,-1 , 0
       0     .12       0  226.72     .07       0     240    .045       0
   263.3     .12       0  409.19     .06       0  556.67     .12       0
#XS Ineff= 2 , 0
                          304.24          804.62
Permanent Ineff=
       F       F
Bank Sta=240,263.3
XS Rating Curve= 0 ,0
Exp/Cntr=0.3,0.1

Type RM Length L Ch R = 1 ,25704.9 ,395.1,397.3,399.3
XS GIS Cut Line= 3
      2337288.26      381746.349     2337317.774      381685.585
     2337796.941      381428.641
#Sta/Elev= 30
       0  850.48   89.25  836.85   103.5  834.52   127.5  829.28   175.5  815.27
   195.5  810.28  205.58806.4656   215.5  802.28   222.4  797.72   227.5  794.71
   231.5  793.94   235.5  794.13   243.5  796.92   279.4  798.56   291.4  797.67
   299.4  798.86   315.4  797.65  329.96 798.542  362.85798.9165   375.4  799.14
   387.4  800.41   395.4  802.13   415.4  809.84   435.4  819.11  454.33825.6983
   471.3  829.88   491.3  833.55  535.14839.6324   579.3  846.91   611.3  850.68
#Mann= 9 ,-1 , 0
       0     .06       0   89.25     .12       0  205.58     .08       0
   222.4    .045       0   243.5     .08       0  329.96     .12       0
  362.85     .06       0  454.33     .12       0  535.14     .06       0
Bank Sta=222.4,243.5
XS Rating Curve= 0 ,0
Exp/Cntr=0.3,0.1

Type RM Length L Ch R = 1 ,25307.6 ,413.1,414.7,416.3
XS GIS Cut Line= 3
     2337449.718      381959.891     2337798.677      381796.696
     2337875.066      381680.377
#Sta/Elev= 30
       0  842.04    35.7  835.21    71.5  829.96    87.4  826.71    99.3   825.1
   111.2  821.62   131.1  817.24   150.9  811.73   158.9   808.5   170.8  805.04
   182.7  799.73   190.6  797.44   214.5  795.62   250.2   794.3   305.8  795.12
   309.8  794.91   317.7   793.4   329.6  790.72   333.6  791.04   337.6  792.19
  339.67  793.83   345.5   798.8   349.5  800.61   369.4  806.92   385.2  810.83
   432.9   824.8  454.84829.3213   480.7  832.39   504.5   836.8   524.4  839.83
#Mann= 4 ,-1 , 0
       0     .12       0   317.7    .045       0  339.67     .12       0
  454.84     .06       0
Bank Sta=317.7,339.67
XS Rating Curve= 0 ,0
Exp/Cntr=0.3,0.1

Type RM Length L Ch R = 1 ,24892.9 ,186.8,187.6,188.3
XS GIS Cut Line= 3
     2337533.052      382246.349     2337974.024      382097.044
     2338107.704      382006.766
#Sta/Elev= 30
       0  839.06    59.7  830.61   107.4  824.87   135.3  819.79   155.2  814.25
   175.1   807.1     183  803.73     195   800.4   206.9  795.68   214.9  793.62
   234.8  791.77   290.5  791.76   314.4  789.85   326.3  787.42   330.3  787.08
   334.2  787.24   338.2  788.14   342.8  789.98   350.2  793.42   362.1  798.05
   397.9  816.35   421.8  825.78   429.8  828.42   441.7  831.51   465.6  836.48
   481.3  838.78   493.1     839   552.1  843.87   583.6   847.4   626.9  853.14
#Mann= 3 ,-1 , 0
       0     .12       0   314.4    .045       0   342.8     .12       0
#XS Ineff= 2 , 0
          279.46  796.33
Permanent Ineff=
       F       F
Bank Sta=314.4,342.8
XS Rating Curve= 0 ,0
Exp/Cntr=0.3,0.1

Type RM Length L Ch R = 1 ,24705.3 ,335.1,334.4,335.8
XS GIS Cut Line= 3
     2337684.755      382384.411     2338030.448      382278.467
     2338160.656      382233.328
#Sta/Elev= 30
       0  825.47    19.9   822.5    31.8  821.28    43.7  818.39    63.6  812.42
    67.5  811.49    75.5  810.64   103.3  801.23   135.1  792.08     143  791.06
   166.9  789.85   206.6  789.67   210.6  789.47   216.8  788.24   230.4  785.96
   234.4  786.03   238.4  786.91   242.4  788.95   246.3  791.93   254.3  795.86
   266.2  802.67   282.1  810.37   305.9  820.56   313.9  824.63   321.8  827.62
   349.6  835.68   377.3  840.34   400.9  840.65   436.4  842.93   499.4  844.45
#Mann= 3 ,-1 , 0
       0     .12       0   216.8    .045       0   242.4     .12       0
Bank Sta=216.8,242.4
XS Rating Curve= 0 ,0
Exp/Cntr=0.3,0.1

Type RM Length L Ch R = 1 ,24370.9 ,249.6,252.3,253
XS GIS Cut Line= 3
     2337763.954      382696.002     2338140.691      382574.474
     2338201.454      382534.544
#Sta/Elev= 30
       0  832.14      20  829.29      36  826.63      64  820.89      76   819.1
      88   816.4     112  809.04     132  801.31     144  796.02   151.9  792.96
   155.9  791.53   159.9  790.61   167.9   789.5   179.9  788.42   187.9  787.99
   199.9  788.09   203.9  787.49   210.6  785.14   215.9  783.65   219.9  783.11
   235.9  785.41   243.9  786.33   255.9   786.4   275.9  789.62   307.9  799.42
   347.9  809.99   359.9  812.91   399.7   821.1   426.5  825.07   468.6   829.9
#Mann= 3 ,-1 , 0
       0     .12       0   210.6    .045       0   235.9     .12       0
Bank Sta=210.6,235.9
XS Rating Curve= 0 ,0
Exp/Cntr=0.3,0.1

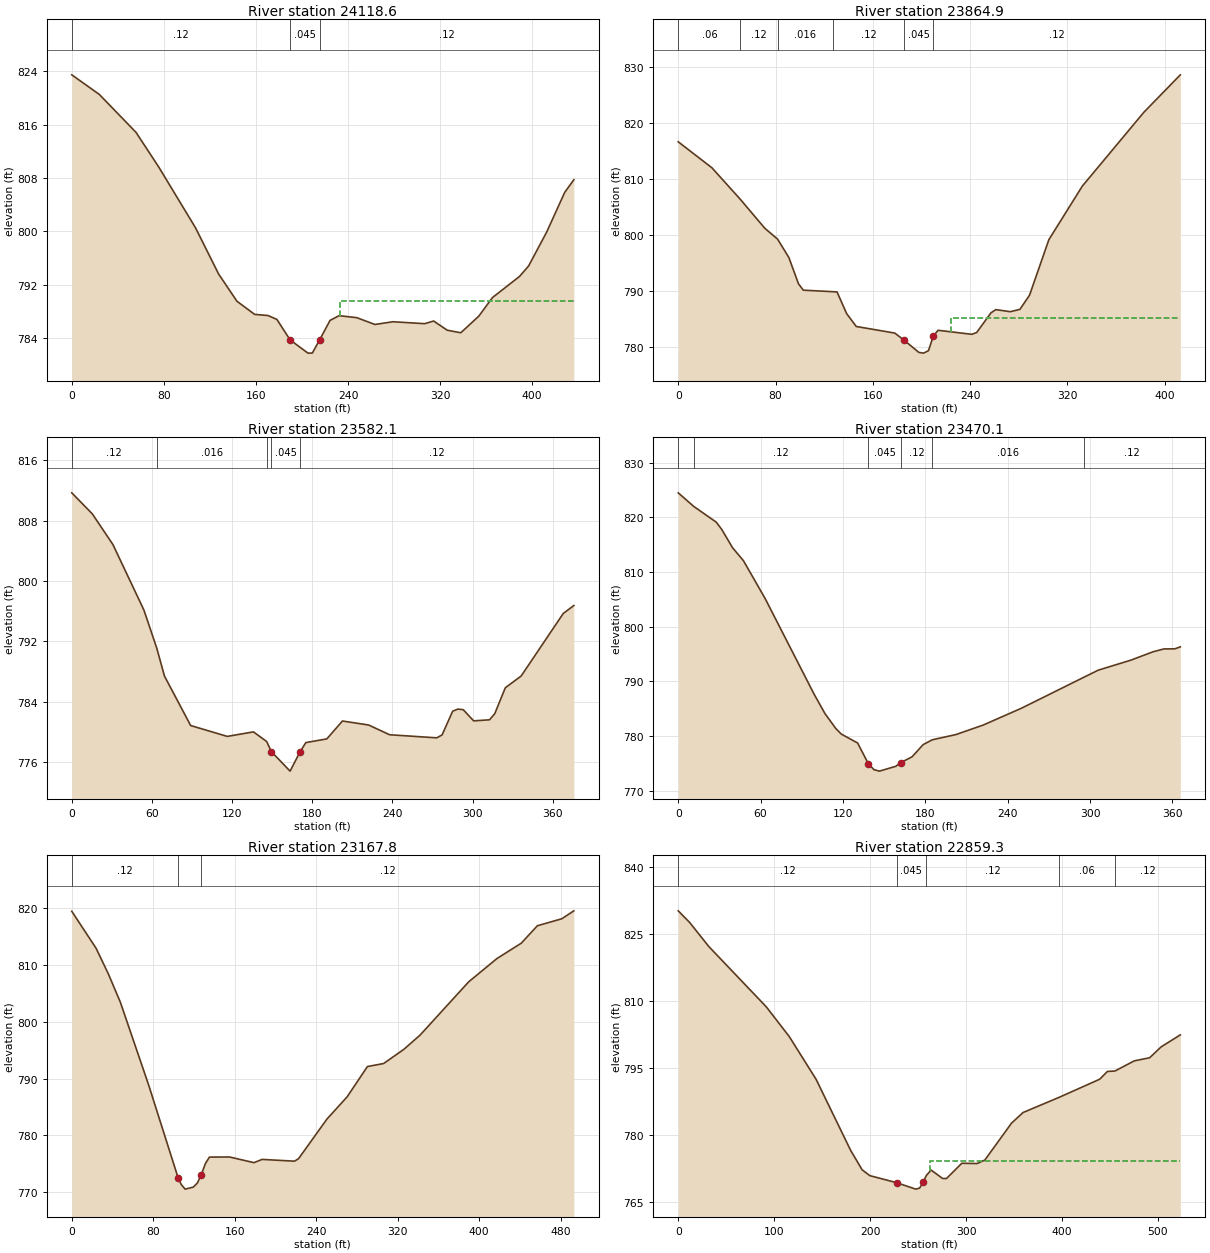
Type RM Length L Ch R = 1 ,24118.6 ,269.4,253.7,236.1
XS GIS Cut Line= 4
     2337843.816      382807.113     2337977.496      382859.196
     2338074.078      382832.328     2338209.495      382695.609
#Sta/Elev= 30
       0  823.44    23.9  820.51    55.8  814.83    75.7   809.6   107.6  800.51
   127.5  793.64   143.5  789.54   158.9  787.57   170.5   787.4   178.2  786.82
   189.7  783.75   205.2  781.77     209  781.78   215.4  783.77   224.4  786.67
   232.2  787.38   247.6  787.08   263.4  786.06   279.1  786.47   306.6  786.18
   314.4  786.58   326.2   785.2     338  784.82   353.7  787.32   365.5  790.09
     389  793.25   396.9  794.82   412.6   799.9   428.3  805.85   436.2  807.73
#Mann= 3 ,-1 , 0
       0     .12       0   189.7    .045       0   215.4     .12       0
#XS Ineff= 2 , 0
                          232.99          789.57
Permanent Ineff=
       F       F
Bank Sta=189.7,215.4
XS Rating Curve= 0 ,0
Exp/Cntr=0.3,0.1

Type RM Length L Ch R = 1 ,23864.9 ,238.2,282.7,327.7
XS GIS Cut Line= 3
     2338130.068       383045.87     2338343.759      382755.958
     2338394.391      382741.182
#Sta/Elev= 30
       0  816.68    27.7  812.04   51.17806.3831    71.2  801.24   81.71799.2978
      91  796.01    98.9  791.32   102.9  790.18  127.32 789.911   130.6  789.87
   138.5     786   146.4   783.7   178.1  782.52     186   781.2   197.9  779.07
   201.8  778.94   205.8  779.38   209.8     782   213.7  783.02   241.4   782.3
   245.4  782.61   257.2  786.14   261.2  786.71   273.1  786.34     281  786.76
   288.9  789.28   304.8   799.2   332.4  808.79   382.8  821.92   412.9  828.64
#Mann= 6 ,-1 , 0
       0     .06       0   51.17     .12       0   81.71    .016       0
  127.32     .12       0     186    .045       0   209.8     .12       0
#XS Ineff= 2 , 0
                          224.65          785.15
Permanent Ineff=
       F       F
Bank Sta=186,209.8
XS Rating Curve= 0 ,0
Exp/Cntr=0.3,0.1

Type RM Length L Ch R = 1 ,23582.1 ,120.8,112,102.6
XS GIS Cut Line= 4
     2338184.755       383058.89     2338253.612      383050.117
     2338394.391      383174.776     2338485.537      383250.297
#Sta/Elev= 30
       0  811.69    15.4   808.9    30.8  804.84      54  796.16   63.59791.1324
    69.4  787.41      89  780.86   116.4  779.42     136  780.02  145.87778.7435
  149.42   777.4   163.4  774.82   170.9  777.38   175.2   778.6   190.9  779.09
   202.6  781.46   222.2  780.93   237.9  779.64   273.2  779.23   277.2  779.62
   285.1  782.76     289  783.04     293  782.96   300.8  781.48   312.7  781.62
   316.6  782.43   324.5  785.86   336.4  787.43   367.9  795.71   375.8  796.76
#Mann= 5 ,-1 , 0
       0     .12       0   63.59    .016       0  145.87     .12       0
  149.42    .045       0   170.9     .12       0
Bank Sta=149.42,170.9
XS Rating Curve= 0 ,0
Exp/Cntr=0.3,0.1

Type RM Length L Ch R = 1 ,23470.1 ,325.1,302.3,279.9
XS GIS Cut Line= 4
     2338153.505      383198.213     2338271.995      383206.026
     2338330.589      383230.765     2338466.005      383354.463
#Sta/Elev= 30
       0  824.46   11.28821.9809    27.7   819.1    31.7  817.77    39.6  814.42
    47.5  812.06    63.3  805.15      99  787.66   106.9  784.12   114.8  781.39
   118.8  780.37   130.7  778.74   138.6  774.91   142.6  773.87   146.6   773.6
   158.5  774.48   162.1  775.15   170.4  776.22   178.4  778.44  185.06779.3287
   202.3  780.28   222.2  782.02   250.1   785.1  295.92790.8032     306  792.05
   329.9  793.89   345.8   795.4   353.8  795.93   361.8  795.95   365.8  796.31
#Mann= 6 ,-1 , 0
       0     .06       0   11.28     .12       0   138.6    .045       0
   162.1     .12       0  185.06    .016       0  295.92     .12       0
Bank Sta=138.6,162.1
XS Rating Curve= 0 ,0
Exp/Cntr=0.3,0.1

Type RM Length L Ch R = 1 ,23167.8 ,320.1,308.5,297.4
XS GIS Cut Line= 2
     2338204.927      383565.794     2338644.163      383341.835
#Sta/Elev= 30
       0  819.37    23.9  812.87    35.8  808.42    47.7  803.41    75.6   788.8
   104.6  772.46   107.4  771.41   111.3  770.57   119.3  770.92   123.3  771.64
   127.2  773.11   131.2  775.05   135.2   776.2   155.1  776.21   178.9  775.22
   186.9  775.79   218.7  775.48   222.7  775.92   250.5  782.86   270.4  786.78
   290.3   792.1   306.2  792.63     326  795.11     342  797.62   389.7  806.97
   417.5  811.07   441.4  813.77   457.2  816.83   481.1  818.05     493  819.45
#Mann= 3 ,-1 , 0
       0     .12       0   104.6    .045       0   127.2     .12       0
Bank Sta=104.6,127.2
XS Rating Curve= 0 ,0
Exp/Cntr=0.3,0.1

Type RM Length L Ch R = 1 ,22859.3 ,354.8,372.8,389.7
XS GIS Cut Line= 3
     2338344.684      383830.695     2338432.357      383803.641
     2338692.991      383459.602
#Sta/Elev= 30
       0  830.26      12  827.63    31.9  822.25    91.8  808.73   115.7  802.08
   143.7  792.49   179.7  776.56   191.7  772.19   199.7  770.88   227.6   769.3
   247.6  767.85   251.6  768.08   255.6   769.5   258.5  770.86   263.6  772.13
   275.6  770.24   279.6  770.22   295.6  773.65   311.6  773.59   319.6  774.36
   347.5  782.66   359.5  785.03  397.39788.4617   439.4   792.5   447.4  794.24
  455.23794.3366   475.4  796.61   491.4  797.31   503.4  799.75   523.4  802.44
#Mann= 5 ,-1 , 0
       0     .12       0   227.6    .045       0   258.5     .12       0
  397.39     .06       0  455.23     .12       0
#XS Ineff= 2 , 0
                          262.64          774.18
Permanent Ineff=
       F       F
Bank Sta=227.6,255.6
XS Rating Curve= 0 ,0
Exp/Cntr=0.3,0.1

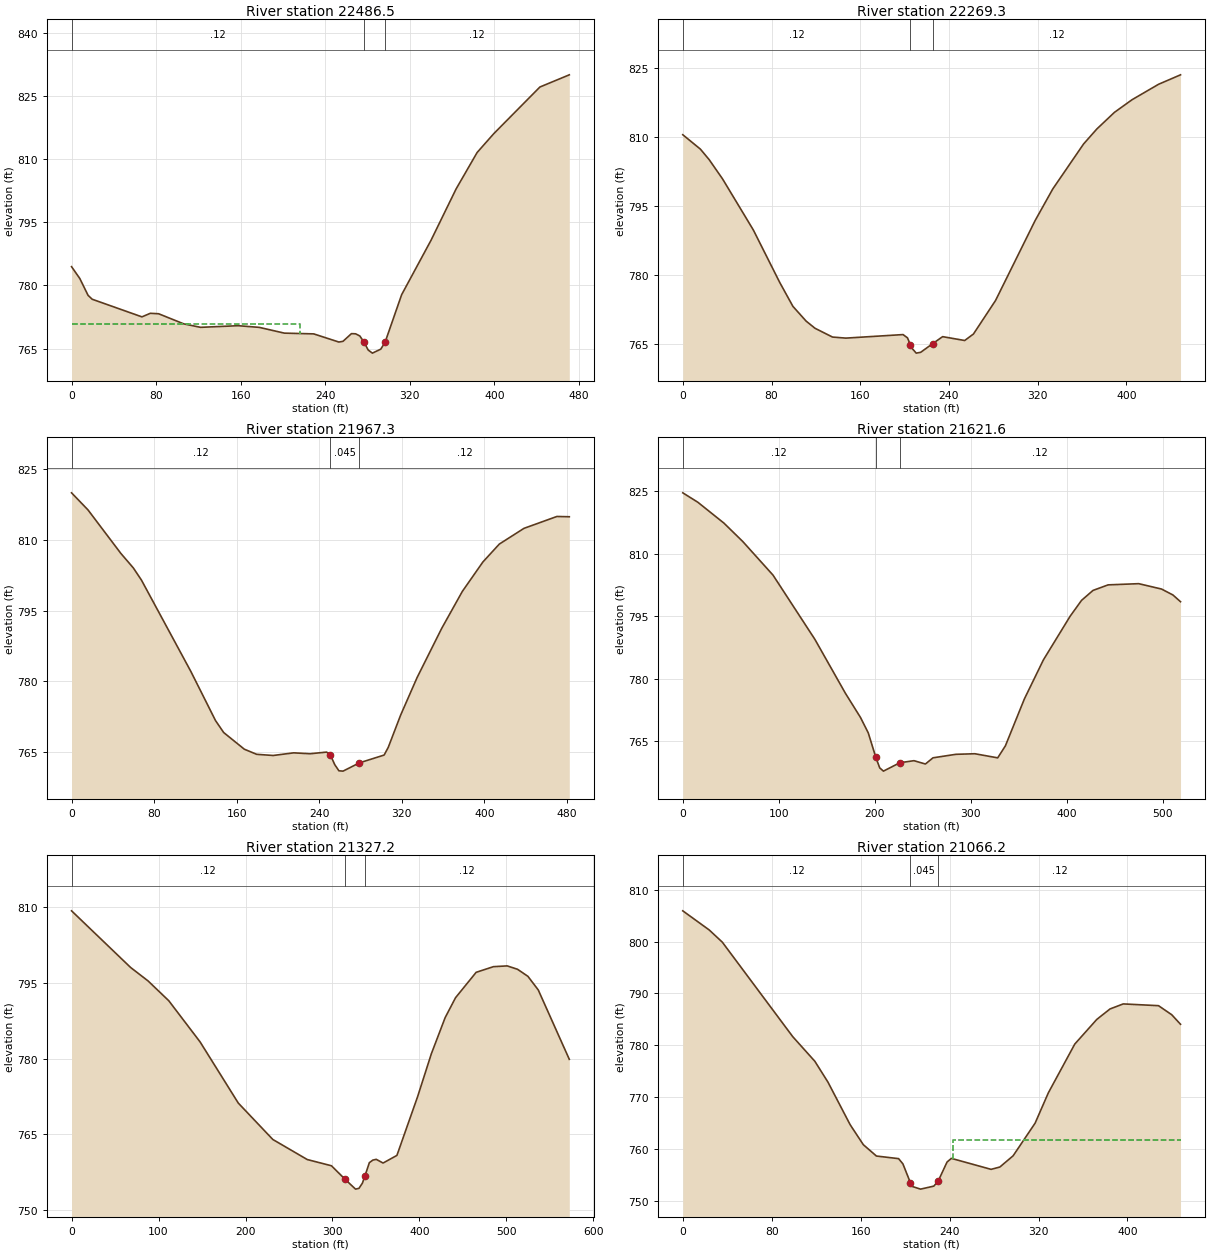
Type RM Length L Ch R = 1 ,22486.5 ,216.4,217.2,217.9
XS GIS Cut Line= 3
     2338546.852      383997.436     2338572.313      383949.056
     2338976.466      383849.619
#Sta/Elev= 30
       0  784.48     7.8  781.67    15.6  777.67    19.5  776.73    66.6  772.53
    74.5  773.38    82.4  773.27   106.2  770.86   122.1  770.04   157.7  770.43
   177.6  770.03   201.3  768.66   229.1  768.48   252.9  766.54   256.8  766.71
   264.8  768.54   268.7   768.5   272.7  767.99   276.6  766.55   280.6  764.65
   284.6   763.9   292.5  764.84   296.6  766.47   312.3  777.82   340.1  790.77
   363.8  802.98   383.7  811.66   399.5  816.16   443.1  827.25   470.9  830.15
#Mann= 3 ,-1 , 0
       0     .12       0   276.6    .045       0   296.6     .12       0
#XS Ineff= 2 , 0
           216.3  770.92
Permanent Ineff=
       F       F
Bank Sta=276.6,296.6
XS Rating Curve= 0 ,0
Exp/Cntr=0.3,0.1

Type RM Length L Ch R = 1 ,22269.3 ,305.9,302.1,298.2
XS GIS Cut Line= 2
     2338582.314      384147.536     2339021.767       384056.39
#Sta/Elev= 30
       0  810.54    15.9   807.4    23.8  805.11    35.8  800.94    63.6   789.8
    87.4  778.37    99.3  773.15   111.2  769.94   119.2  768.38     135  766.46
     147  766.23   198.6     767   202.6  766.29   205.2   764.8   206.5  764.06
   210.5  762.96   214.5  763.14   225.2     765   234.3  766.55   254.2  765.71
   262.1  767.13     282  774.42   317.7  791.84   333.6  798.72   361.4  808.53
   373.3  811.78   389.2  815.41   405.1  818.17     429  821.53   448.8  823.59
#Mann= 3 ,-1 , 0
       0     .12       0   205.2    .045       0   225.2     .12       0
Bank Sta=205.2,225.2
XS Rating Curve= 0 ,0
Exp/Cntr=0.3,0.1

Type RM Length L Ch R = 1 ,21967.3 ,345.1,345.7,361.2
XS GIS Cut Line= 2
     2338623.546      384453.525     2339083.616      384309.211
#Sta/Elev= 30
       0  820.04    15.9  816.42    47.8  807.17    59.8  804.11    67.7  801.52
   115.6  782.11   139.5  771.68   147.4  769.15   167.4  765.61   179.3  764.53
   195.3  764.28   215.2  764.84   231.1  764.65   247.1     765   250.7   764.4
     255  762.33     259  761.03     263  760.96   278.9  762.72   302.8  764.37
   306.8     766   318.8  772.85   334.7   780.8   358.6  791.27   378.6  799.12
   398.5  805.36   414.4  809.16   438.3   812.5   470.2  815.02   482.2  814.96
#Mann= 3 ,-1 , 0
       0     .12       0   250.7    .045       0   278.9     .12       0
Bank Sta=250.7,278.9
XS Rating Curve= 0 ,0
Exp/Cntr=0.3,0.1

Type RM Length L Ch R = 1 ,21621.6 ,297.6,294.4,274.6
XS GIS Cut Line= 3
     2338674.545      384686.815     2338748.329      384694.411
     2339164.996      384540.331
#Sta/Elev= 30
       0  824.66    15.6  822.41    42.9  817.37    62.5  812.95      94  804.87
   137.6  789.43   169.4  776.46   185.2  770.61   193.2  766.93   201.1  761.04
   205.1  758.53     209  757.75   226.1  759.77   240.8  760.26   252.7  759.46
   260.6  760.95   284.4  761.79   304.2  761.93     328  760.94     336  763.83
   355.8  775.12   375.6   784.5   403.4  794.98   415.3   798.8   427.2  801.19
     443  802.53   474.8  802.82   498.6  801.53   510.5   800.1   518.4  798.48
#Mann= 3 ,-1 , 0
       0     .12       0   201.1    .045       0   226.1     .12       0
Bank Sta=201.1,226.1
XS Rating Curve= 0 ,0
Exp/Cntr=0.3,0.1

Type RM Length L Ch R = 1 ,21327.2 ,265.8,261,255.4
XS GIS Cut Line= 3
     2338809.093      385029.697     2338921.626       384869.61
     2339260.482      384705.261
#Sta/Elev= 30
       0  809.22    67.9  798.02    87.9  795.37   111.8  791.44   147.8   783.3
   191.7  771.21   231.4  764.01     271  760.04   298.8  758.81   314.6  756.12
   326.5  754.19   330.5  754.35   334.4  755.37  337.36  756.81   342.4  759.42
   346.3  759.92   350.3  760.08   358.2  759.35   374.1  760.86   397.9  772.48
   413.7  780.96   429.6  788.12   441.5  792.04   465.2  797.06   485.1  798.18
   500.9  798.33   512.8  797.66   524.7  796.27   536.6  793.58   572.3  779.86
#Mann= 3 ,-1 , 0
       0     .12       0   314.6    .045       0  337.36     .12       0
Bank Sta=314.6,337.36
XS Rating Curve= 0 ,0
Exp/Cntr=0.3,0.1

Type RM Length L Ch R = 1 ,21066.2 ,315,293.9,272.4
XS GIS Cut Line= 3
     2338918.116      385132.228     2339019.067      385112.302
     2339292.519      384902.209
#Sta/Elev= 30
       0  805.96    23.8  802.26    35.6   799.9    98.9  781.66   118.8   776.9
   130.6  772.87   150.5  764.67   162.4  760.79   174.2   758.6   194.1   758.1
     198  757.09  204.75  753.44     206  752.75   213.9  752.21   225.8  752.79
   229.8   753.8   237.7  757.44   241.6  758.15   277.3  756.03   285.2  756.48
   297.1  758.64   316.9  764.95   328.8   770.8   352.6  780.23   372.4  784.99
   384.3  787.01   396.2  787.98   427.9  787.64   439.8  785.89   447.7  784.05
#Mann= 3 ,-1 , 0
       0     .12       0  204.75    .045       0   229.8     .12       0
#XS Ineff= 2 , 0
                          242.62          761.79
Permanent Ineff=
       F       F
Bank Sta=204.75,229.8
XS Rating Curve= 0 ,0
Exp/Cntr=0.3,0.1

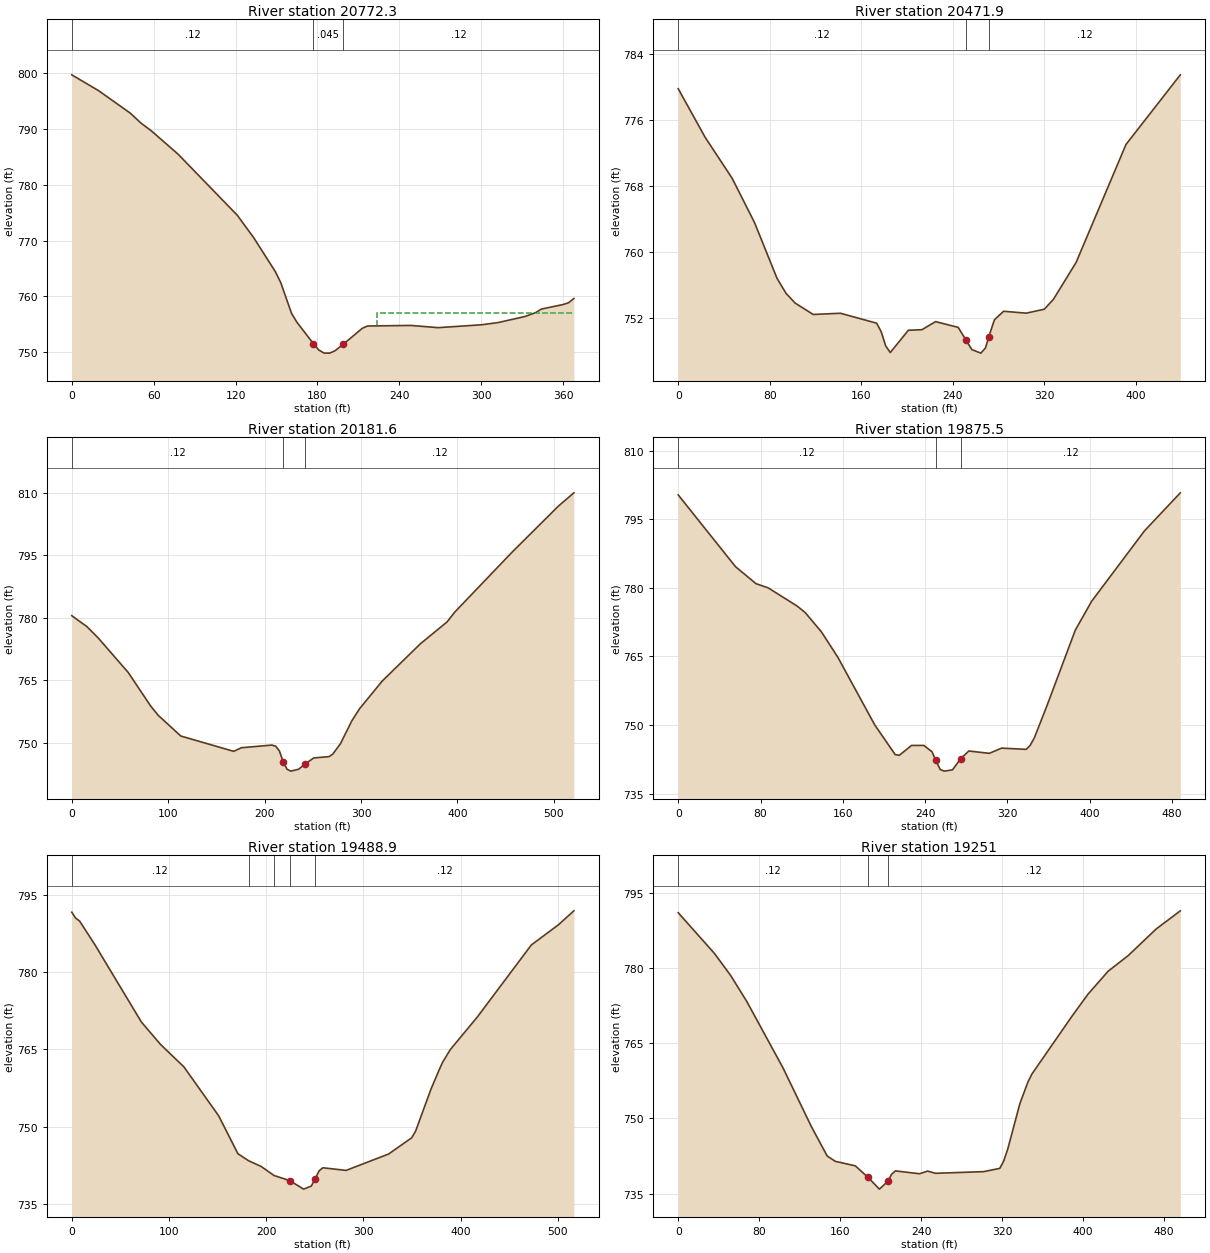
Type RM Length L Ch R = 1 ,20772.3 ,293.5,300.4,307.4
XS GIS Cut Line= 3
     2339330.578      385417.935     2339316.255      385321.581
      2339338.39      385052.049
#Sta/Elev= 30
       0  799.76    19.5  796.94    42.9  792.88    50.6  791.12    58.4  789.68
    77.9  785.51   121.3  774.54   133.2  770.55   149.1  764.44   153.1  762.45
     161  756.94     165  755.32     177  751.51   180.9  750.37   184.9   749.8
   188.9   749.8   192.9  750.23     199  751.42   212.8  754.25   216.7  754.67
   248.5  754.77   268.4  754.37   300.2  754.89   312.2  755.28   332.1  756.38
     340  757.09     344  757.71   359.9  758.52   363.9  758.84   367.8   759.6
#Mann= 3 ,-1 , 0
       0     .12       0     177    .045       0     199     .12       0
#XS Ineff= 2 , 0
                          223.88          756.99
Permanent Ineff=
       F       F
Bank Sta=177,199
XS Rating Curve= 0 ,0
Exp/Cntr=0.3,0.1

Type RM Length L Ch R = 1 ,20471.9 ,267.4,290.2,313.1
XS GIS Cut Line= 3
     2339476.411      385455.695     2339544.119       385408.82
     2339680.838      385079.393
#Sta/Elev= 30
       0  779.83    23.5  773.93    47.1  768.95    66.7  763.56    86.3   756.8
    94.2  754.96   102.2  753.77     118  752.38   141.8  752.53   173.5  751.32
   177.5  750.27   181.4  748.56   185.4  747.75   201.2  750.46   213.1  750.53
     225  751.51   244.8  750.81   251.6  749.27   256.7  748.11   264.6  747.68
   268.6   748.3   271.6   749.7   276.5  751.74   284.5  752.77   304.3  752.54
   320.1  753.02   328.1  754.23   347.9  758.71   391.5  773.05     439  781.52
#Mann= 3 ,-1 , 0
       0     .12       0   251.6    .045       0   271.6     .12       0
Bank Sta=251.6,271.6
XS Rating Curve= 0 ,0
Exp/Cntr=0.3,0.1

Type RM Length L Ch R = 1 ,20181.6 ,303.7,306.1,308.6
XS GIS Cut Line= 4
     2339524.588      385570.279      2339650.89      385509.081
     2339890.474      385441.372     2340012.869      385489.549
#Sta/Elev= 30
       0  780.49    15.6   777.9    27.3  775.19    58.5  766.91    81.9  758.83
    89.7  756.62   113.1  751.66     168  747.99   175.9  748.85   207.5  749.49
   211.5  749.23   215.4  748.08   219.4  745.43   223.3   743.7   227.3  743.25
   235.2  743.69   242.2  744.97     251  746.41   266.8  746.72   270.8  747.35
   278.7  749.82   290.5   755.3   298.4  758.16   322.1  764.85   361.6  773.76
   389.3     779   397.3  781.36   457.1   795.8   504.9  806.77   520.8  809.93
#Mann= 3 ,-1 , 0
       0     .12       0   219.4    .045       0   242.2     .12       0
Bank Sta=219.4,242.2
XS Rating Curve= 0 ,0
Exp/Cntr=0.3,0.1

Type RM Length L Ch R = 1 ,19875.5 ,392,386.6,381
XS GIS Cut Line= 3
      2339494.64      385824.185     2339933.442       385746.06
     2339975.109      385738.247
#Sta/Elev= 30
       0  800.31    55.7  784.62    75.6  780.91    87.6  779.97   115.4  776.04
   123.4   774.6   139.3  770.34   155.2  764.81     191  750.04   210.9  743.54
   214.9  743.38   226.8  745.54   238.8  745.54   246.7  744.16   250.2  742.33
   254.7  740.27   258.7  739.92   266.6   740.2   274.6  742.64   282.5  744.32
   302.4  743.81   314.4  744.95   338.3  744.68   342.2  745.58   346.2   747.2
   358.2  754.07     386  770.74   401.9  777.06   453.4  792.49   488.1  800.77
#Mann= 3 ,-1 , 0
       0     .12       0   250.2    .045       0   274.6     .12       0
Bank Sta=250.2,274.6
XS Rating Curve= 0 ,0
Exp/Cntr=0.3,0.1

Type RM Length L Ch R = 1 ,19488.9 ,244.2,237.9,231.6
XS GIS Cut Line= 3
     2339615.734      386186.164      2339769.38      386165.331
     2340104.015      386028.612
#Sta/Elev= 30
       0  791.66       4  790.51       8  789.96    23.8  785.34    71.6  770.32
    91.4  765.94   115.3  761.61   151.1  752.09   170.9  744.72  181.86 743.352
   194.8  742.24  208.16740.4722   224.2  739.49   238.5  737.83   246.4  738.42
   250.4  739.85   254.4  741.38   258.3  741.98   282.2  741.47   325.9  744.65
   349.7  747.81   353.7  749.09   369.6   757.3   377.5  760.82   381.5   762.5
   389.4  764.95   417.2  771.29   472.8   785.3   500.6  789.21   516.5  791.93
#Mann= 5 ,-1 , 0
       0     .12       0  181.86     .06       0  208.16     .12       0
   224.2    .045       0   250.4     .12       0
Bank Sta=224.2,250.4
XS Rating Curve= 0 ,0
Exp/Cntr=0.3,0.1

Type RM Length L Ch R = 1 ,19251   ,307.9,318.4,327.5
XS GIS Cut Line= 3
     2339752.453      386428.352     2339855.317      386397.102
     2340160.005      386156.216
#Sta/Elev= 30
       0  791.06    35.8  782.93    51.8  778.53    67.7  773.35   103.5  760.08
   131.3  748.45   147.1   742.5   155.1  741.43   174.9  740.53   187.3  738.26
   198.7  735.88   207.3  737.49   210.6  738.81   214.5  739.52   238.3  738.95
   246.2  739.48   254.2  739.04   301.7  739.37   317.6  740.03   321.5   741.5
   325.5  743.91   337.4  752.92   345.3  757.22   349.3  758.85   388.9   770.4
   404.8  774.82   424.6  779.38   444.4   782.5   472.1  787.82   495.9  791.44
#Mann= 3 ,-1 , 0
       0     .12       0   187.3    .045       0   207.3     .12       0
Bank Sta=187.3,207.3
XS Rating Curve= 0 ,0
Exp/Cntr=0.3,0.1

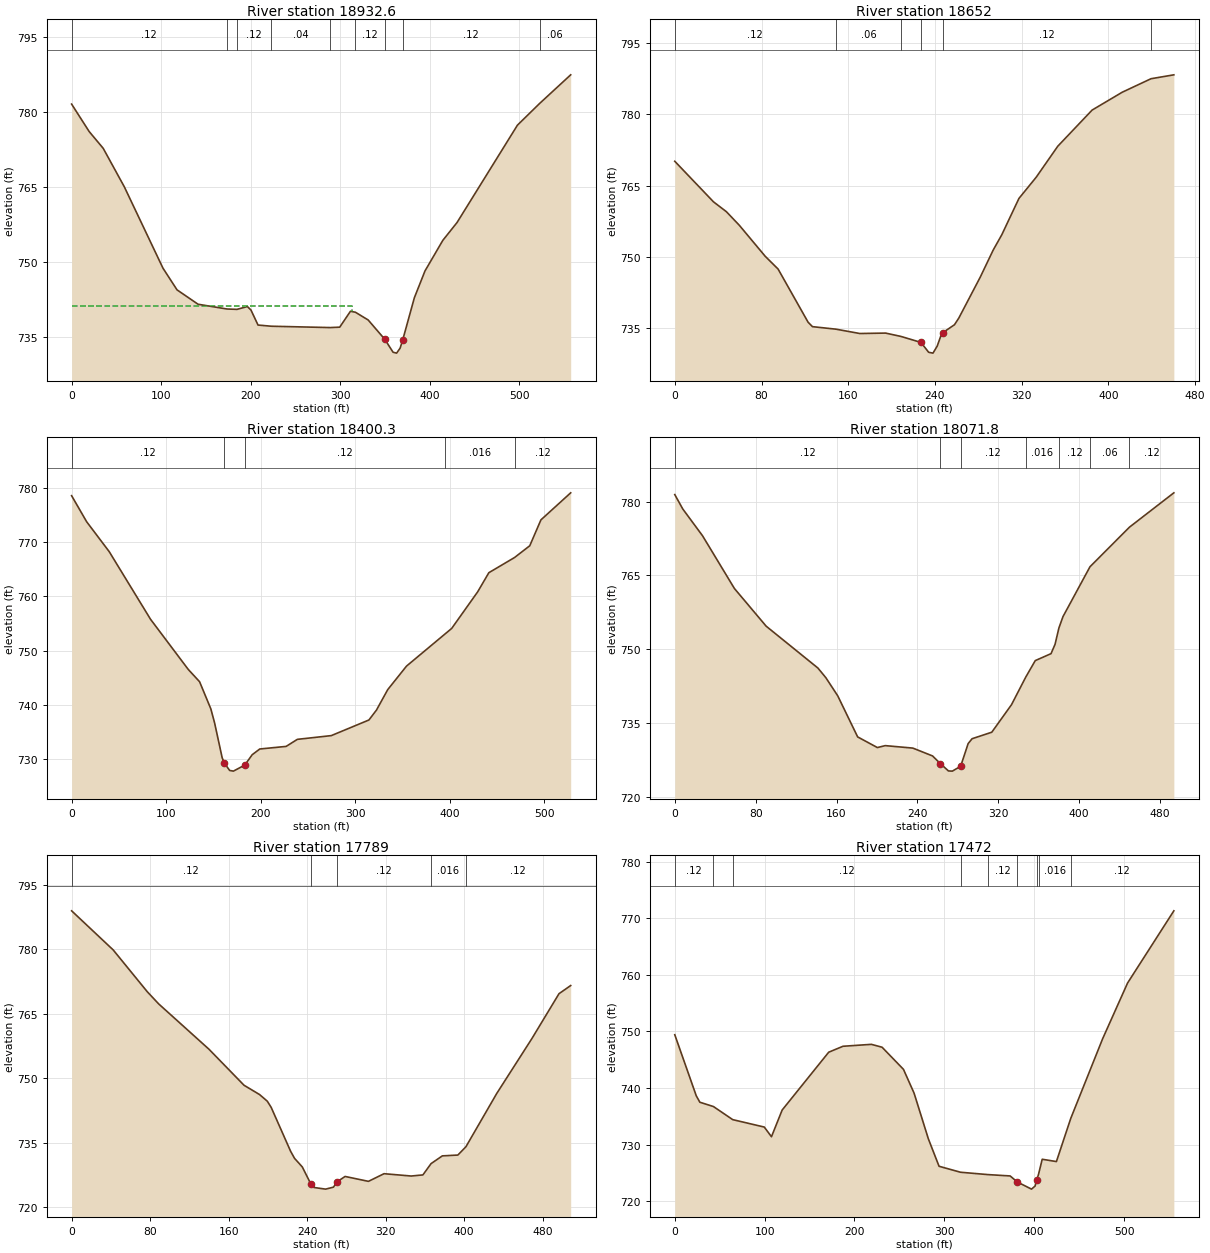
Type RM Length L Ch R = 1 ,18932.6 ,279.3,280.5,282.5
XS GIS Cut Line= 3
     2339778.494      386506.477     2339949.067      386576.789
     2340299.328      386447.883
#Sta/Elev= 30
       0  781.53    19.6  776.06    35.3  772.71    58.9  765.03   102.1   748.8
   117.8  744.48   141.3  741.61  173.57740.6621  184.74740.5868   196.4  741.15
   200.4  740.46   208.3  737.46  223.34737.2243  288.99736.9574   299.6  737.04
   311.6  740.21  317.13740.0156   331.4  738.47     350  734.61   359.2  732.04
   363.2  731.86   367.1  732.86     370  734.49     383   742.9   394.9  748.26
   414.8  754.35   430.7  757.91   498.2  777.33  523.02781.6658   557.7  787.37
#Mann= 9 ,-1 , 0
       0     .12       0  173.57     .06       0  184.74     .12       0
  223.34     .04       0  288.99     .06       0  317.13     .12       0
     350    .045       0     370     .12       0  523.02     .06       0
#XS Ineff= 2 , 0
          313.48  741.33
Permanent Ineff=
       F       F
Bank Sta=350,370
XS Rating Curve= 0 ,0
Exp/Cntr=0.3,0.1

Type RM Length L Ch R = 1 ,18652   ,249.4,251.7,248.9
XS GIS Cut Line= 2
     2339950.369      386843.716     2340396.984      386731.737
#Sta/Elev= 30
       0  770.12    35.7  761.56    47.6  759.48    59.5  756.62    83.4  750.07
    95.3  747.37     123  736.14     127  735.21  148.64734.6765   170.7  733.76
   194.5  733.85  208.67733.1441   227.1  731.88   234.2   729.8   238.2  729.62
   242.1  731.11   246.1  733.67   247.1  733.92     258  735.61     262  737.01
   281.8  745.66   293.7  751.36   301.7  754.62   317.5  762.28   333.4  766.75
   353.3  773.29     385  780.93   412.8   784.7  439.35787.5475   460.4  788.37
#Mann= 6 ,-1 , 0
       0     .12       0  148.64     .06       0  208.67     .12       0
   227.1    .045       0   247.1     .12       0  439.35     .06       0
Bank Sta=227.1,247.1
XS Rating Curve= 0 ,0
Exp/Cntr=0.3,0.1

Type RM Length L Ch R = 1 ,18400.3 ,339.7,328.6,318
XS GIS Cut Line= 3
     2339977.713      387049.445     2340372.244       386971.32
     2340486.828      387023.404
#Sta/Elev= 30
       0  778.56    15.9  773.76    39.8  768.24    83.6  755.75   123.4  746.53
   135.4  744.26   147.3  739.26   151.3  736.66   159.3  730.24   161.7  729.24
   167.2   727.9   171.2  727.77   183.2  728.88   191.1   730.8   199.1  731.85
     227  732.33   238.9  733.63   274.8  734.32   314.6   737.2   322.6  739.03
   334.5   742.8   354.4  747.14  395.01753.0434   402.2  754.09   429.7  760.84
   441.5  764.36  468.69 767.159   484.8  769.33   496.6   774.1   528.1  779.09
#Mann= 5 ,-1 , 0
       0     .12       0   161.7    .045       0   183.2     .12       0
  395.01    .016       0  468.69     .12       0
Bank Sta=161.7,183.2
XS Rating Curve= 0 ,0
Exp/Cntr=0.3,0.1

Type RM Length L Ch R = 1 ,18071.8 ,276,282.8,289.9
XS GIS Cut Line= 4
     2340038.911      387359.341     2340208.182      387295.539
     2340339.692      387204.393     2340484.224      387154.914
#Sta/Elev= 30
       0   781.4     7.9  778.49    27.5  773.04      59  762.36    90.4  754.72
   141.6  746.23   149.4  744.29   161.2   740.6   180.9  732.27   200.4  730.11
   208.2   730.5   235.5     730     255  728.41   262.8  726.84   270.7  725.37
   274.6  725.33   282.8  726.32   290.2  730.91   294.1   731.9   313.6  733.22
   333.1   738.8  347.23744.4092   356.6  747.74   372.2  749.15   376.2  751.05
  379.99754.3541     384  756.65  410.72766.7629  449.76774.7928   493.7  781.76
#Mann= 7 ,-1 , 0
       0     .12       0   262.8    .045       0   282.8     .12       0
  347.23    .016       0  379.99     .12       0  410.72     .06       0
  449.76     .12       0
Bank Sta=262.8,282.8
XS Rating Curve= 0 ,0
Exp/Cntr=0.3,0.1

Type RM Length L Ch R = 1 ,17789   ,317,317,316.3
XS GIS Cut Line= 3
     2340021.984      387477.831     2340114.432      387505.174
     2340506.359       387377.57
#Sta/Elev= 30
       0  788.96    42.4  779.85    77.1  770.13    88.7   767.3     140  756.74
   175.7  748.36   191.5   746.2   199.4  744.65   203.4   743.2   223.2  732.98
   227.2  731.34   235.1  729.34   243.6  725.46     247  724.56   258.9  724.18
   266.8  724.64   270.8  725.92   278.7  727.13   302.5  725.99   318.4  727.77
   346.1  727.23     358  727.49   366.3 730.116   377.8  731.92   393.6  732.11
  401.82 734.039   433.3  746.47     469   759.2   496.7  769.67   508.6  771.57
#Mann= 5 ,-1 , 0
       0     .12       0   243.6    .045       0   270.8     .12       0
   366.3    .016       0  401.82     .12       0
Bank Sta=243.6,270.8
XS Rating Curve= 0 ,0
Exp/Cntr=0.3,0.1

Type RM Length L Ch R = 1 ,17472   ,170.4,159.1,147.5
XS GIS Cut Line= 3
     2340072.765      387845.018     2340214.692      387742.154
     2340576.671      387626.268
#Sta/Elev= 30
       0  749.42    23.9  738.63    27.9  737.49   43.02736.7266   64.51734.4114
    99.6   733.1   107.6  731.39   119.5  736.11   171.3  746.33   187.2  747.38
   218.8  747.72   230.7  747.21   254.5   743.3   266.3   739.1   282.2  731.02
   294.1  726.17  317.99725.1143  348.36   724.7   373.2  724.46   381.2  723.39
     397  722.13     401  722.68  402.82  723.75  404.83 724.762   408.9  727.41
   424.7     727  440.73734.6563   476.2  748.73   503.9  758.56   555.4  771.32
#Mann= 9 ,-1 , 0
       0     .12       0   43.02     .06       0   64.51     .12       0
  317.99     .06       0  348.36     .12       0   381.2    .045       0
  402.82     .12       0  404.83    .016       0  440.73     .12       0
Bank Sta=381.2,402.82
XS Rating Curve= 0 ,0
Exp/Cntr=0.3,0.1