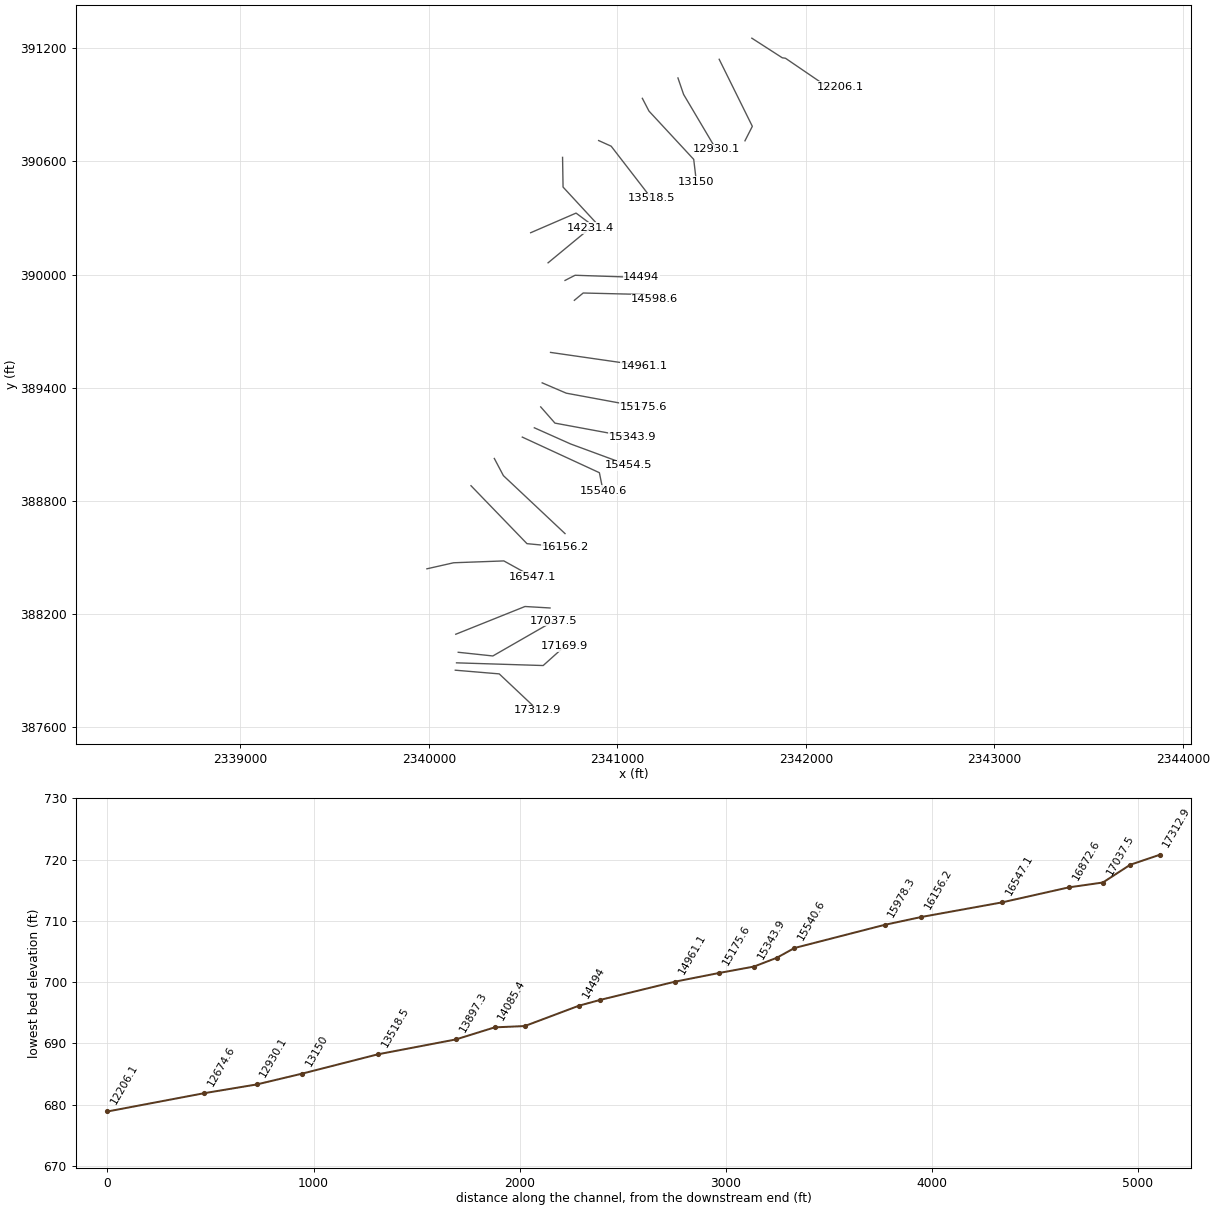
HEC-RAS study MOUNTAINRN.prj: MOUNTAINRN

--- MOUNTAINRN.g01 (geometry) --- (continued)

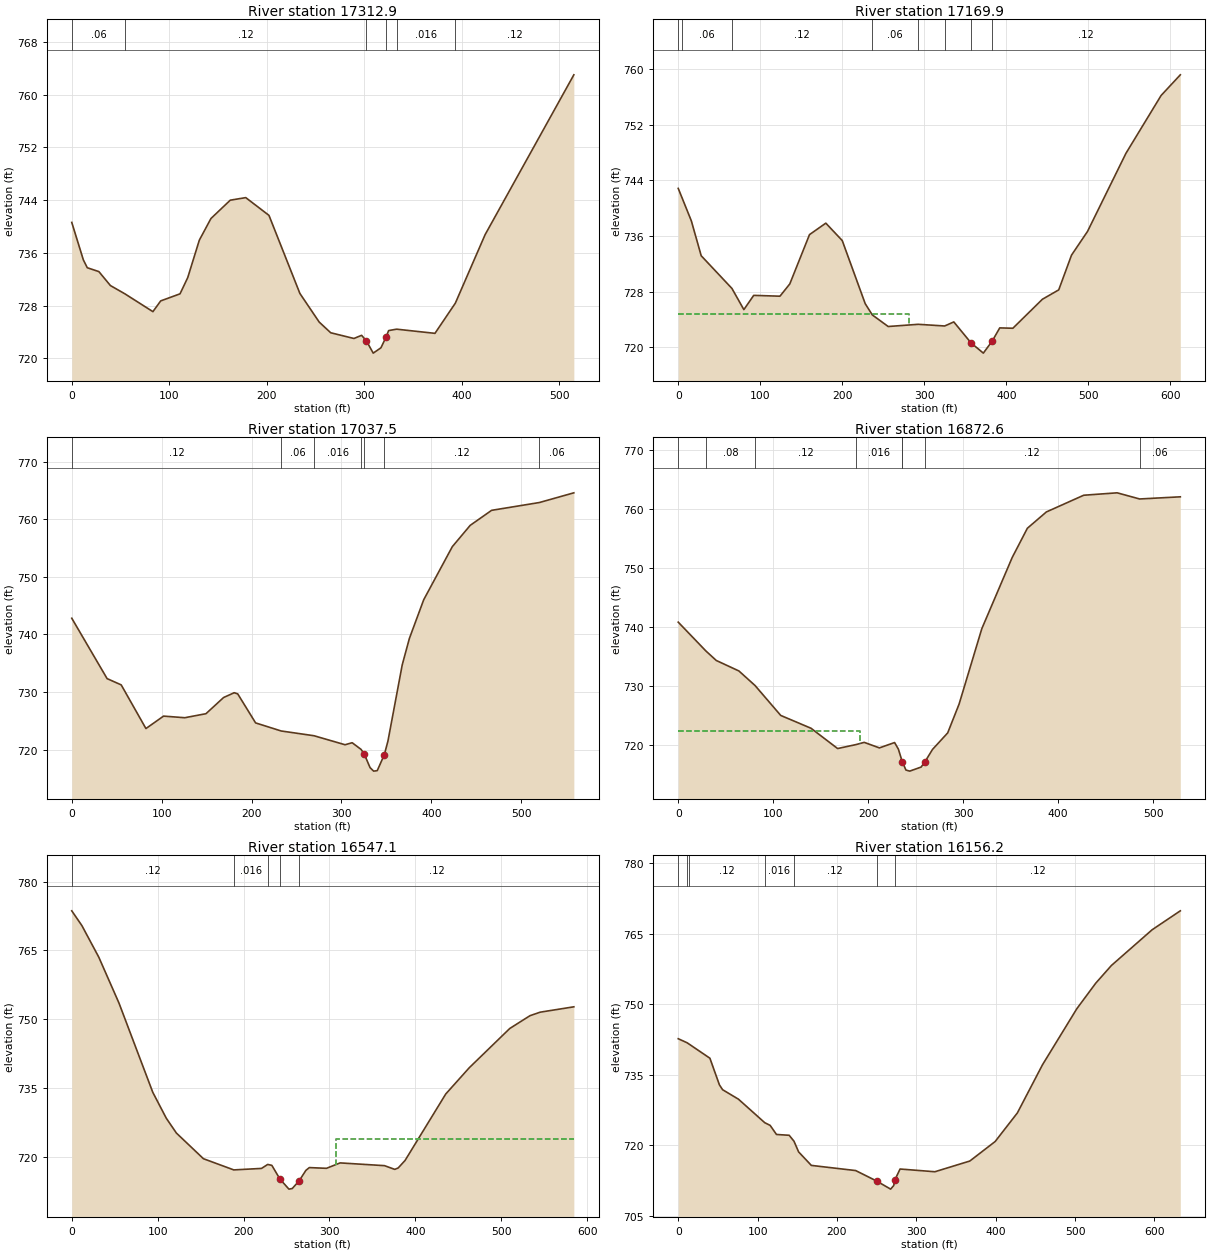
Type RM Length L Ch R = 1 ,17312.9 ,125.3,143.1,160.9
XS GIS Cut Line= 3
     2340140.484      387901.686     2340373.557      387882.154
     2340577.984      387689.446
#Sta/Elev= 30
       0  740.61    11.9  734.92    15.9  733.74    27.8  733.15    39.6  731.04
   54.56729.7729    83.2  727.08    91.2  728.71     111  729.78   118.9  732.24
   130.8  737.92   142.7   741.2   162.5  743.98   178.4  744.37   202.2  741.68
   233.9  729.84   253.7   725.5   265.5  723.88   289.3  723.01   297.2  723.49
   302.1  722.64   309.1  720.79     317   721.6   322.1  723.17   324.9  724.21
  333.09724.4211   372.4  723.79  393.34728.3791   423.8  738.75   514.8  762.99
#Mann= 6 ,-1 , 0
       0     .06       0   54.56     .12       0   302.1    .045       0
   322.1     .12       0  333.09    .016       0  393.34     .12       0
Bank Sta=302.1,322.1
XS Rating Curve= 0 ,0
Exp/Cntr=0.3,0.1

Type RM Length L Ch R = 1 ,17169.9 ,117.8,132.4,147
XS GIS Cut Line= 3
     2340146.995      387940.748      2340606.63      387926.425
     2340719.912      388027.988
#Sta/Elev= 30
       0  742.86    4.23741.6293      16  738.18      28  733.17   65.45728.4678
      80  725.42      92  727.47     124  727.35     136  729.12     160  736.21
   179.9  737.86   199.9  735.36   227.9  726.28  236.52724.6616   255.9  722.99
  292.54723.3052  324.81723.0656   335.9  723.65     357  720.62   371.9  719.16
   382.8  720.91   391.9  722.79   407.9  722.74   443.9  726.91   463.8  728.26
   479.4  733.26   498.9  736.67   545.7   747.9   588.6  756.23     612   759.2
#Mann= 8 ,-1 , 0
       0     .12       0    4.23     .06       0   65.45     .12       0
  236.52     .06       0  292.54    .016       0  324.81     .12       0
     357    .045       0   382.8     .12       0
#XS Ineff= 2 , 0
          281.26  724.86
Permanent Ineff=
       F       F
Bank Sta=357,382.8
XS Rating Curve= 0 ,0
Exp/Cntr=0.3,0.1

Type RM Length L Ch R = 1 ,17037.5 ,168.7,164.9,161.1
XS GIS Cut Line= 3
     2340156.109      387996.738     2340339.703      387977.206
     2340663.922      388163.404
#Sta/Elev= 30
       0  742.81    39.3  732.33      55  731.24    82.5  723.66   102.1  725.82
   125.7  725.54   149.3  726.24   168.9  729.05   180.7  729.88   184.6  729.68
   204.5  724.64  232.91  723.24  269.48722.4134     304  720.85   311.9   721.2
  321.74720.0508   325.3  719.26   331.8  716.88   335.8  716.27   339.8  716.35
   347.7  719.14   351.7  721.48   367.6  734.72   375.6  739.32   391.5  746.02
   423.3  755.23   443.2  758.93     467  761.54  520.21762.8967   558.5  764.58
#Mann= 7 ,-1 , 0
       0     .12       0  232.91     .06       0  269.48    .016       0
  321.74     .12       0   325.3    .045       0   347.7     .12       0
  520.21     .06       0
Bank Sta=325.3,347.7
XS Rating Curve= 0 ,0
Exp/Cntr=0.3,0.1

Type RM Length L Ch R = 1 ,16872.6 ,333.9,325.5,316.8
XS GIS Cut Line= 3
     2340143.078      388092.414     2340510.265      388239.549
     2340643.078      388231.737
#Sta/Elev= 30
       0  740.81   29.07735.9188      40   734.3    63.9  732.51   80.87730.0372
   107.9  724.95   139.8  722.77   167.8  719.32  187.36720.0002   195.8  720.37
   211.8  719.43   227.8  720.34   231.8  719.21  235.66 717.181   235.9  717.09
   239.7  715.67   243.7  715.48   255.7  716.17   259.7  717.05   267.7  719.17
   283.7  721.98   295.7  726.88   319.6  739.69   351.6   751.8   367.6  756.78
   387.6  759.55   426.9  762.39   462.1   762.8  485.78761.7549   528.6  762.12
#Mann= 8 ,-1 , 0
       0     .12       0   29.07     .08       0   80.87     .12       0
  187.36    .016       0  235.66     .12       0   235.9    .045       0
   259.7     .12       0  485.78     .06       0
#XS Ineff= 2 , 0
          191.01  722.32
Permanent Ineff=
       F       F
Bank Sta=235.9,259.7
XS Rating Curve= 0 ,0
Exp/Cntr=0.3,0.1

Type RM Length L Ch R = 1 ,16547.1 ,413.5,391,368
XS GIS Cut Line= 4
     2339990.005      388439.467     2340131.793      388471.551
     2340398.056      388481.293     2340549.243      388397.808
#Sta/Elev= 30
       0  773.62    11.8   770.4    31.4  763.55      55  753.52    94.3  734.11
     110  728.47   121.8  725.23   153.3  719.64  188.63717.2036   220.9  717.53
   228.1 718.394   232.9   718.2   242.4   715.2   252.8  713.02   256.7  713.15
   264.7  714.83   272.6  717.11   276.6  717.71   296.5  717.55   312.4  718.73
   364.1  718.13     376  717.32     380  717.63     388  719.26   435.4  733.74
   462.8  739.46   509.9     748   533.5  750.79   545.3  751.55   584.5  752.72
#Mann= 5 ,-1 , 0
       0     .12       0  188.63    .016       0   228.1     .12       0
   242.4    .045       0   264.7     .12       0
#XS Ineff= 2 , 0
                          307.32          723.84
Permanent Ineff=
       F       F
Bank Sta=242.4,264.7
XS Rating Curve= 0 ,0
Exp/Cntr=0.3,0.1

Type RM Length L Ch R = 1 ,16156.2 ,177.2,177.9,178.8
XS GIS Cut Line= 3
     2340223.807      388880.174     2340520.682      388572.883
     2340725.109      388553.352
#Sta/Elev= 30
       0  742.65   10.89741.8138   13.54741.5229    39.9   738.5    51.9  732.83
    55.9   731.8    75.9  729.78  108.98724.7815   115.8  724.21   123.8  722.27
   139.8   722.1  145.86 720.829   151.7  718.56   167.7  715.69   223.6  714.59
   249.9  712.37   267.6  710.64   271.5   711.4  273.17  712.68   279.5  714.92
   323.4  714.34   367.4  716.62   399.3  720.77   427.3  726.86   458.9  737.09
   502.3  749.06     526  754.46   545.8  758.24   597.1  765.84   632.6  769.87
#Mann= 7 ,-1 , 0
       0     .12       0   10.89     .06       0   13.54     .12       0
  108.98    .016       0  145.86     .12       0   249.9    .045       0
  273.17     .12       0
Bank Sta=249.9,273.17
XS Rating Curve= 0 ,0
Exp/Cntr=0.3,0.1

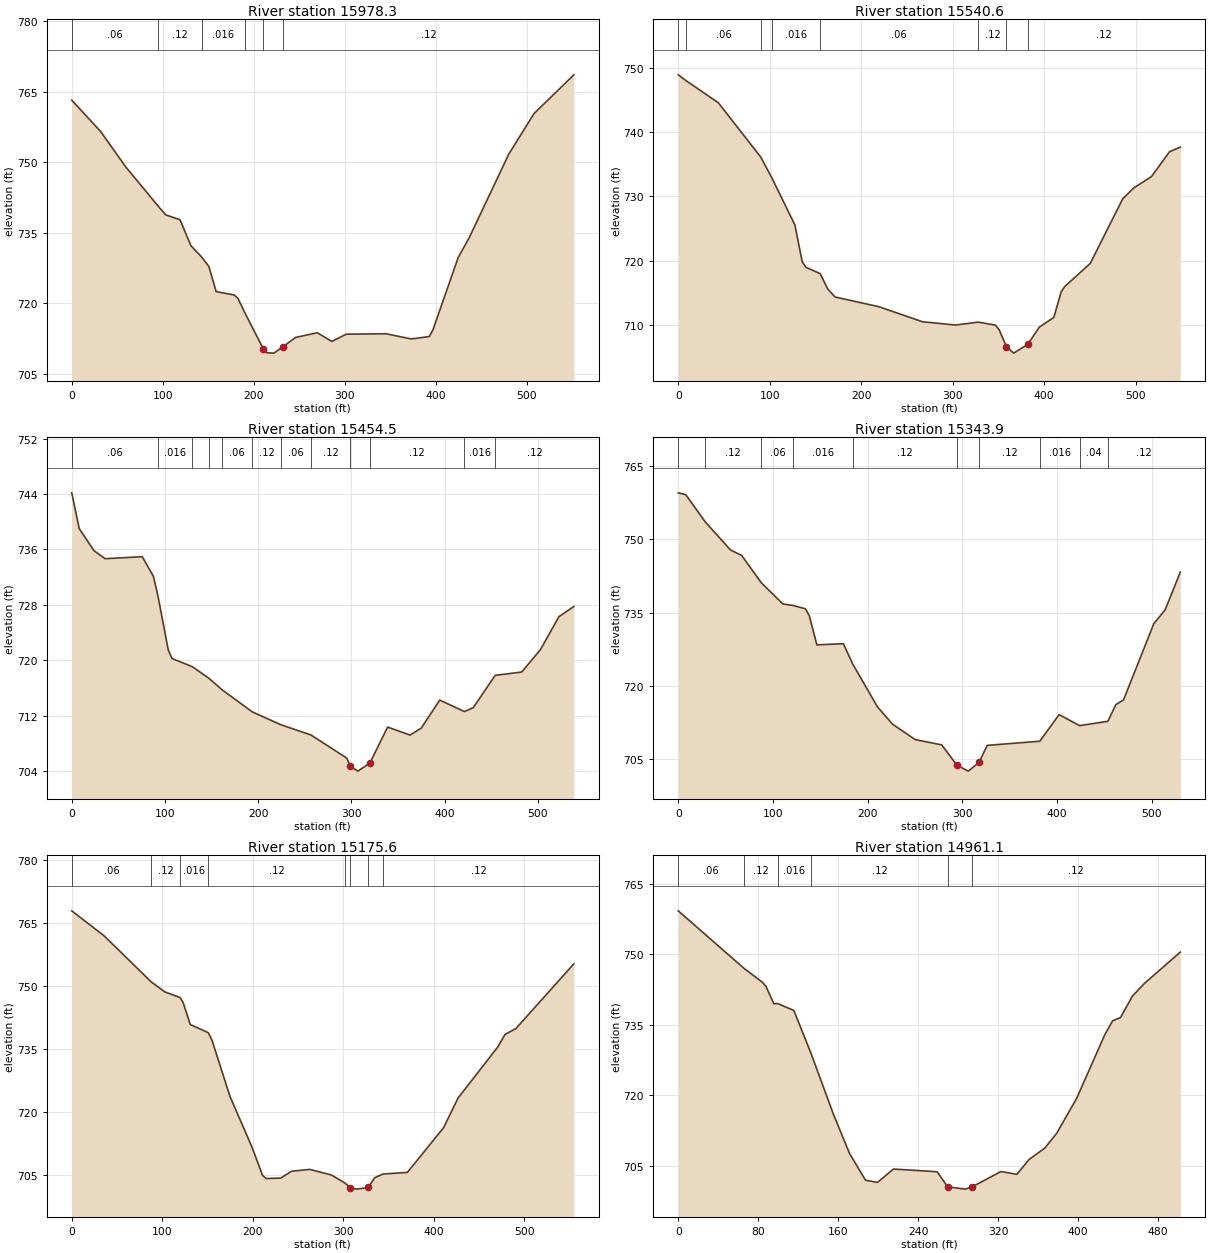
Type RM Length L Ch R = 1 ,15978.3 ,427.5,437.7,446.1
XS GIS Cut Line= 3
     2340347.505      389024.706     2340395.682       388933.56
     2340722.505      388626.268
#Sta/Elev= 30
       0  763.22    31.7  756.56    59.5  748.97   95.07740.6341   103.1  738.82
     119  737.75   130.9  732.24   143.1 729.736   150.7   727.8   158.7  722.46
   178.5  721.74   182.5  721.06  190.07718.0026   210.3  710.34   214.2  709.44
   222.2  709.36   232.2  710.75     246   712.7   269.8   713.7   285.7  711.85
   301.6  713.39   345.3  713.49     373  712.38   392.9   712.9   396.9  714.34
   424.7  729.76   436.6  733.89   480.2  751.73     508  760.38   551.7  768.62
#Mann= 6 ,-1 , 0
       0     .06       0   95.07     .12       0   143.1    .016       0
  190.07     .12       0   210.3    .045       0   232.2     .12       0
Bank Sta=210.3,232.2
XS Rating Curve= 0 ,0
Exp/Cntr=0.3,0.1

Type RM Length L Ch R = 1 ,15540.6 ,83.9,86.1,88.6
XS GIS Cut Line= 3
     2340495.942      389137.987     2340904.796      388949.185
     2340924.328      388852.831
#Sta/Elev= 30
       0  748.97    8.46748.0698    43.8  744.62   90.32 736.126  102.07732.9728
   127.5  725.56   135.5  719.83   139.5  718.97  155.06717.9757   163.4  715.58
   171.4  714.33   219.2  712.82     267  710.47   302.9  709.96  327.94710.4114
   346.7  709.94   350.7  709.24   358.7  706.59   366.6  705.58   381.9  706.93
   394.6  709.63   410.5  711.16   418.5  715.13   422.4  715.96   450.3  719.57
   485.7  729.62   497.5   731.3   517.2  733.11   536.9  736.98   548.7   737.7
#Mann= 8 ,-1 , 0
       0     .12       0    8.46     .06       0   90.32     .12       0
  102.07    .016       0  155.06     .06       0  327.94     .12       0
   358.7    .045       0   381.9     .12       0
Bank Sta=358.7,381.9
XS Rating Curve= 0 ,0
Exp/Cntr=0.3,0.1

Type RM Length L Ch R = 1 ,15454.5 ,106.1,110.6,114.8
XS GIS Cut Line= 3
     2340559.744      389187.466     2340752.453      389101.529
     2341059.744      388988.247
#Sta/Elev= 30
       0  744.16       8  738.99    23.9   735.8    35.8  734.65    75.6  734.94
    87.6  732.09   92.59729.1676   103.5  721.48   107.5  720.24  129.29719.0601
  146.71717.4219  161.38715.7101  193.46712.5453  224.07710.6858  256.44709.2061
   294.9  705.87   298.9  704.66   306.9  703.98   319.7  705.14   338.8  710.34
   362.8  709.19   374.8  710.18   394.7  714.24  421.21712.5763   430.7  713.16
  454.13717.8018   482.6  718.29   502.6  721.51   522.5  726.28   538.5  727.75
#Mann= 12 ,-1 , 0
       0     .06       0   92.59    .016       0  129.29     .06       0
  146.71     .12       0  161.38     .06       0  193.46     .12       0
  224.07     .06       0  256.44     .12       0   298.9    .045       0
   319.7     .12       0  421.21    .016       0  454.13     .12       0
Bank Sta=298.9,319.7
XS Rating Curve= 0 ,0
Exp/Cntr=0.3,0.1

Type RM Length L Ch R = 1 ,15343.9 ,168.2,168.2,168.3
XS GIS Cut Line= 3
     2340593.599      389298.143     2340669.119      389212.206
     2341077.974      389136.685
#Sta/Elev= 30
       0   759.5     7.9  759.14   28.59753.5348    55.2  747.81    67.1  746.67
    87.8  741.08   110.5  736.76  121.66736.4348   134.4  735.76   138.4  734.35
   146.4  728.39   174.4  728.62   184.4 724.415   210.4   715.7   226.3  712.16
   250.3     709   278.3  707.92   294.3  703.75   306.3  702.55   317.6  704.33
   326.3  707.82  381.79708.6667   402.2  714.12  423.82711.8605  453.74712.7464
   462.2  716.18   470.2  717.11   502.2  732.71   514.2  735.56   530.2  743.28
#Mann= 10 ,-1 , 0
       0     .08       0   28.59     .12       0    87.8     .06       0
  121.66    .016       0   184.4     .12       0   294.3    .045       0
   317.6     .12       0  381.79    .016       0  423.82     .04       0
  453.74     .12       0
Bank Sta=294.3,317.6
XS Rating Curve= 0 ,0
Exp/Cntr=0.3,0.1

Type RM Length L Ch R = 1 ,15175.6 ,213.5,214.5,215.4
XS GIS Cut Line= 3
     2340601.411      389425.747     2340729.015       389371.06
     2341137.869      389295.539
#Sta/Elev= 30
       0  767.91    35.7  761.95   87.79750.9482   103.1  748.54  119.68747.2234
     123  746.02   130.9  740.78  150.78738.8437   154.8  737.09   174.8   723.6
   198.8  711.68   210.8  704.77   214.8  704.04   230.8  704.14   242.8  705.78
   262.8  706.22   286.8  704.89  301.72702.9668   307.5  701.89   314.7  701.51
   327.5   701.9   334.7  704.25  344.03705.1266   370.7   705.5   410.7  716.16
   426.7  723.24   470.6  735.43   478.6  738.42   490.6  739.82   554.6  755.26
#Mann= 8 ,-1 , 0
       0     .06       0   87.79     .12       0  119.68    .016       0
  150.78     .12       0  301.72    .016       0   307.5    .045       0
   327.5    .016       0  344.03     .12       0
Bank Sta=307.5,327.5
XS Rating Curve= 0 ,0
Exp/Cntr=0.3,0.1

Type RM Length L Ch R = 1 ,14961.1 ,360.6,362.5,364.3
XS GIS Cut Line= 2
     2340645.682      389587.206     2341143.078      389515.591
#Sta/Elev= 30
       0  759.26   65.96747.0102    83.8  744.15    87.7  743.25    95.7   739.5
   99.51739.5476   115.7  738.08  132.95728.9264   155.5   715.9   171.5  707.66
   187.4     702   199.4  701.51   215.4  704.36   255.2  703.84   259.2  703.76
  269.72  700.58   287.2  700.09   293.7  700.53     323  703.83     339  703.24
     351  706.37   366.9  708.82   378.9     712   398.8  719.41   426.8  732.86
   434.7  735.85   442.7  736.59   454.7  741.16   466.6  743.83   502.5  750.48
#Mann= 6 ,-1 , 0
       0     .06       0   65.96     .12       0   99.51    .016       0
  132.95     .12       0  269.72    .045       0   293.7     .12       0
Bank Sta=269.72,293.7
XS Rating Curve= 0 ,0
Exp/Cntr=0.3,0.1

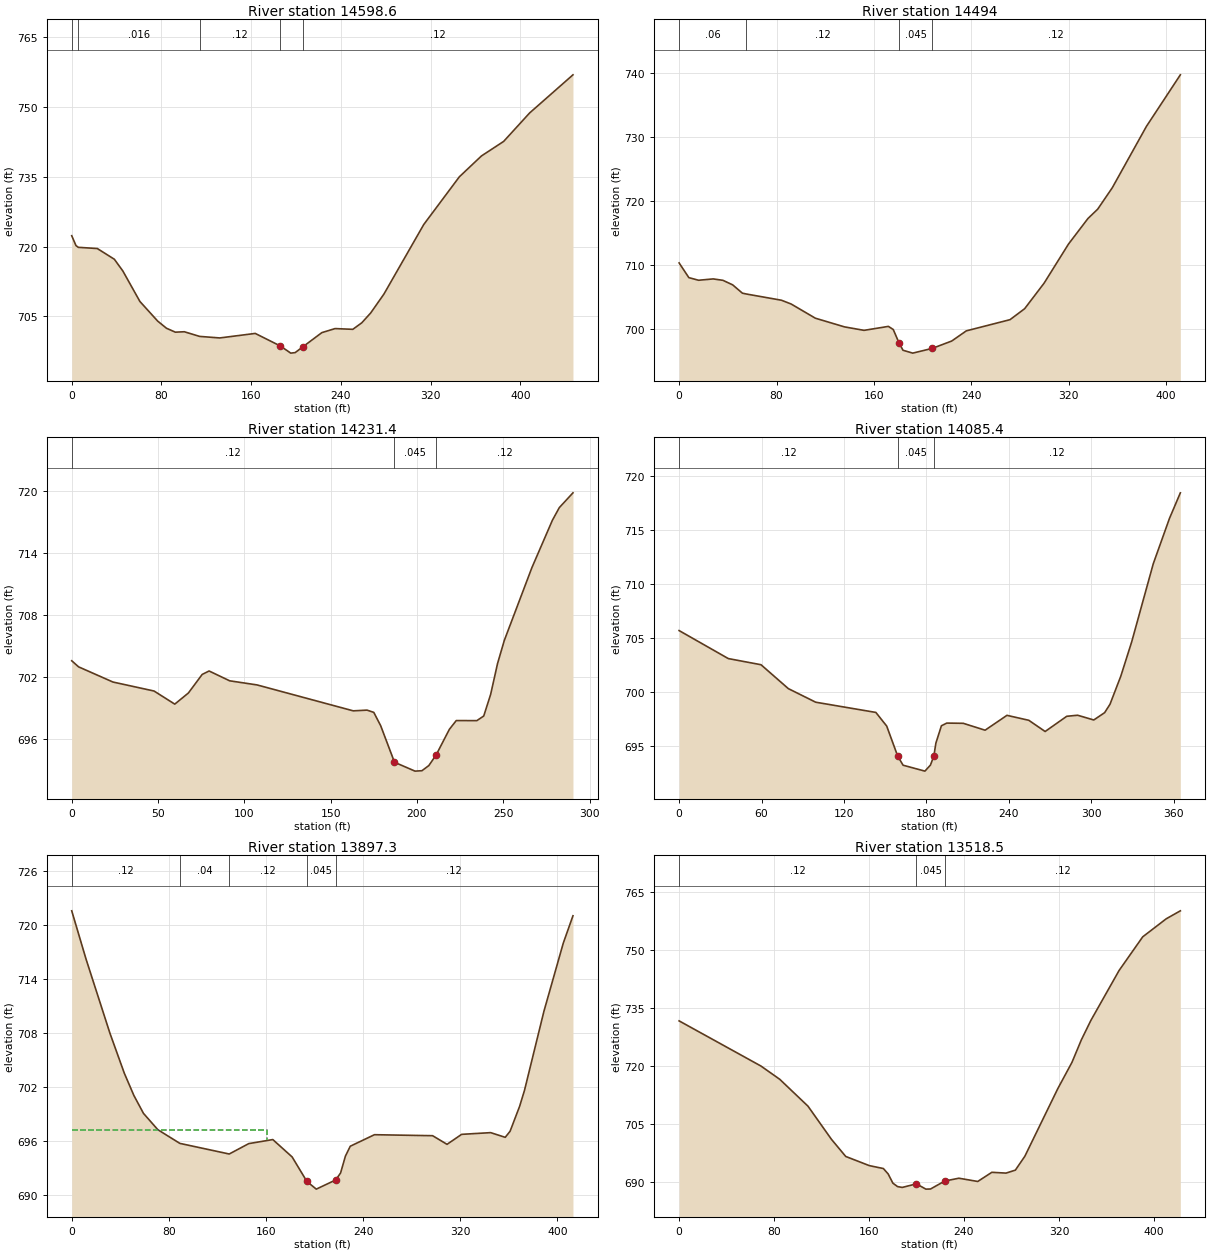
Type RM Length L Ch R = 1 ,14598.6 ,103.8,104.7,104.7
XS GIS Cut Line= 4
     2340771.995      389863.578     2340818.859       389902.31
     2341143.078      389894.497     2341199.067      389868.456
#Sta/Elev= 30
       0  722.33     3.8  720.21    5.88719.8378    22.8  719.58      38  717.28
    45.6  714.75    60.8  708.21    76.6  704.01    84.5  702.46    92.4  701.62
   100.4  701.71  114.01700.7122     132  700.38   163.6  701.35   186.1  698.64
   195.3  697.12   199.2  697.23   206.1  698.48     223  701.52   234.8  702.39
   250.6  702.23   258.6  703.63   266.5  705.73   278.3  709.78   313.9  724.75
   345.6  734.98   365.3  739.46   385.1  742.58   408.3   748.7   446.9  756.88
#Mann= 5 ,-1 , 0
       0     .12       0    5.88    .016       0  114.01     .12       0
   186.1    .045       0   206.1     .12       0
Bank Sta=186.1,206.1
XS Rating Curve= 0 ,0
Exp/Cntr=0.3,0.1

Type RM Length L Ch R = 1 ,14494   ,244.2,262.6,281.6
XS GIS Cut Line= 3
     2340722.516      389969.047     2340775.901       389996.39
     2341127.464      389984.672
#Sta/Elev= 30
       0  710.26       8  707.96      16  707.55      28  707.76      36  707.54
      44  706.83      52  705.53   55.27705.3992      84  704.43      92  703.84
   111.9  701.62   135.9  700.26   151.9  699.72   171.9  700.34   175.9  699.85
   180.6  697.77   183.9  696.61   191.9  696.16   207.9   696.9   223.9  698.05
   235.9  699.64   271.8  701.39   283.8   703.1   299.8   707.1   319.8   713.2
   335.8   717.2   343.8  718.66   355.8  722.01   383.8  731.59   411.7  739.66
#Mann= 4 ,-1 , 0
       0     .06       0   55.27     .12       0   180.6    .045       0
   207.9     .12       0
Bank Sta=180.6,207.9
XS Rating Curve= 0 ,0
Exp/Cntr=0.3,0.1

Type RM Length L Ch R = 1 ,14231.4 ,153.5,146,138.3
XS GIS Cut Line= 2
     2340632.661      390062.466     2340856.619      390247.362
#Sta/Elev= 30
       0  703.53       4  702.94    23.9  701.47    47.7   700.6    59.7  699.33
    67.6  700.41    75.6  702.21    79.6  702.54    91.5  701.59   107.4  701.19
   163.1  698.68   171.1  698.75     175  698.53     179  697.24     187   693.7
   198.9  692.84   202.9  692.88   206.9  693.38   211.1   694.4   218.8  696.89
   222.8  697.74   234.7  697.73   238.7  698.18   242.7  700.27   246.7  703.26
   250.6  705.49   266.6  712.55   278.5  717.15   282.5  718.37   290.4   719.8
#Mann= 3 ,-1 , 0
       0     .12       0     187    .045       0   211.1     .12       0
Bank Sta=187,211.1
XS Rating Curve= 0 ,0
Exp/Cntr=0.3,0.1

Type RM Length L Ch R = 1 ,14085.4 ,219.6,188.1,156.8
XS GIS Cut Line= 3
     2340540.224      390221.998     2340781.109      390326.165
     2340863.141      390264.967
#Sta/Elev= 30
       0  705.68    35.8  703.08    59.6  702.51    79.5  700.29    99.4  699.03
   143.2  698.08   151.1  696.81   159.1  694.02     163  693.18   178.9  692.63
   182.9  693.19  185.37  694.02   186.9  695.24   190.9  696.84   194.8  697.09
   206.8  697.07   222.7  696.43   238.6  697.81   254.5  697.35   266.4  696.31
   282.1  697.72     290  697.82   301.8  697.38   309.7  698.06   313.6  698.84
   321.5  701.46   329.4  704.64   345.1  711.89   356.9   716.1   364.8  718.47
#Mann= 3 ,-1 , 0
       0     .12       0   159.1    .045       0  185.37     .12       0
Bank Sta=159.1,185.37
XS Rating Curve= 0 ,0
Exp/Cntr=0.3,0.1

Type RM Length L Ch R = 1 ,13897.3 ,373.8,378.9,379.3
XS GIS Cut Line= 3
     2340709.495      390621.738     2340712.099      390464.186
     2340885.276      390276.686
#Sta/Elev= 30
       0   721.6    11.8  716.23    31.5  707.98    43.3  703.55    51.2  701.07
    59.1  699.08    70.9  697.27   89.05695.7457  129.71694.5648   145.8  695.72
   165.6  696.17   181.5  694.24   193.7  691.51   201.4  690.66   217.4  691.68
   221.4  692.45   225.4  694.33   229.4  695.43   249.3  696.71   297.2   696.6
   309.1  695.64   321.1  696.75     345  696.94     357  696.42     361  697.09
   368.9  699.88   372.9  701.65   388.9  710.44   404.8     718   412.8  721.05
#Mann= 5 ,-1 , 0
       0     .12       0   89.05     .04       0  129.71     .12       0
   193.7    .045       0   217.4     .12       0
#XS Ineff= 2 , 0
           161.1  697.28
Permanent Ineff=
       F       F
Bank Sta=193.7,217.4
XS Rating Curve= 0 ,0
Exp/Cntr=0.3,0.1

Type RM Length L Ch R = 1 ,13518.5 ,365.1,368.5,375
XS GIS Cut Line= 3
      2340900.89      390710.904     2340967.296      390680.956
     2341180.849       390404.29
#Sta/Elev= 30
       0  731.71      69  720.03    84.8  716.61   108.6  709.66   128.4  701.08
   140.4  696.67   160.2  694.31   172.1  693.55   176.1  692.17   180.1  689.78
     184  688.89     188  688.67   199.9   689.6   207.9  688.23   211.8  688.26
   223.8  690.32   235.7  691.05   251.6  690.21   263.5  692.58   275.4  692.37
   283.3  693.14   291.3  696.73   319.1  714.23     331     721   338.9  726.81
   346.9  731.82   370.7  744.74   390.6  753.43   410.4  758.09   422.3  760.15
#Mann= 3 ,-1 , 0
       0     .12       0   199.9    .045       0   223.8     .12       0
Bank Sta=199.9,223.8
XS Rating Curve= 0 ,0
Exp/Cntr=0.3,0.1

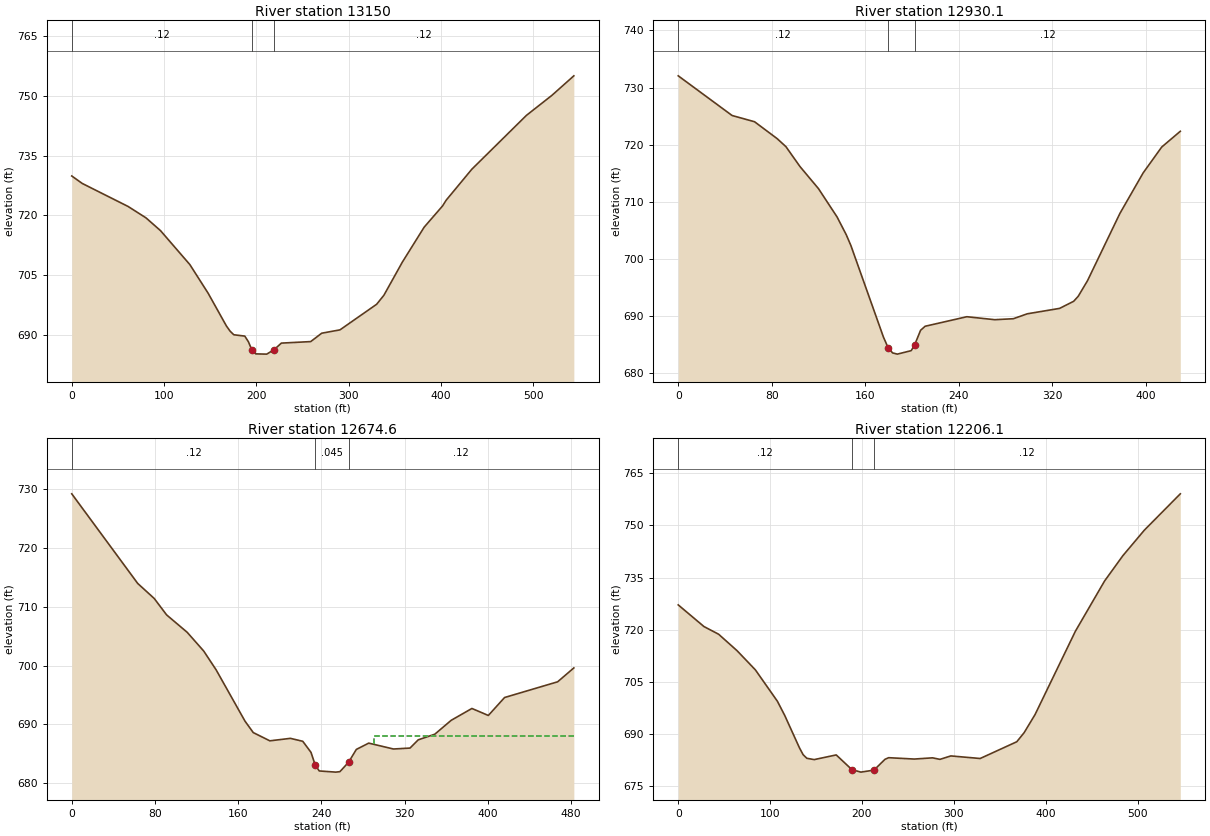
Type RM Length L Ch R = 1 ,13150   ,227.3,219.9,208.2
XS GIS Cut Line= 4
     2341132.661      390934.862     2341167.817      390867.154
     2341405.083        390611.1     2341419.119      390493.456
#Sta/Elev= 30
       0  729.85    11.4  727.97      61  722.19    80.3  719.34    96.1  716.12
   127.9  707.58   147.7  700.38   167.5  692.15   171.5  690.84   175.5  689.94
   187.4   689.6   191.3  688.19   195.3  686.01   199.3  685.13   211.2  685.07
   219.3  686.22     227  687.84   258.8  688.22   270.7  690.33   290.5  691.17
   330.2   697.6   338.1  699.88   357.9  708.14   381.7  716.99   401.6  722.32
   405.5  723.76   433.3  731.55   492.5   745.1   520.2  750.15   543.8  755.03
#Mann= 3 ,-1 , 0
       0     .12       0   195.3    .045       0   219.3     .12       0
Bank Sta=195.3,219.3
XS Rating Curve= 0 ,0
Exp/Cntr=0.3,0.1

Type RM Length L Ch R = 1 ,12930.1 ,256.8,255.5,255.1
XS GIS Cut Line= 3
     2341321.463      391042.935     2341351.411      390955.695
     2341523.286      390665.331
#Sta/Elev= 30
       0  732.05    46.1   725.1    65.3  724.01    84.6  721.06    92.2  719.64
   104.2  716.16     120   712.3   135.9  707.35   143.8  704.22   147.8  702.31
   175.6  686.31   179.6  684.43   183.5  683.52   187.5  683.31   199.4  683.92
   202.3  684.91   207.4  687.48   211.3  688.19     247  689.86   270.9  689.34
   286.8  689.51   298.7  690.37   326.4  691.32   338.4  692.56   342.3  693.43
   350.3  696.18     378  707.95   397.9  715.05   413.8  719.58   429.7  722.34
#Mann= 3 ,-1 , 0
       0     .12       0   179.6    .045       0   202.3     .12       0
Bank Sta=179.6,202.3
XS Rating Curve= 0 ,0
Exp/Cntr=0.3,0.1

Type RM Length L Ch R = 1 ,12674.6 ,452,468.5,529.9
XS GIS Cut Line= 3
     2341540.213      391141.893     2341715.994      390786.424
     2341676.932      390709.602
#Sta/Elev= 30
       0  729.18    63.4  713.95    79.3  711.39    91.2   708.6     111  705.64
   126.9  702.45   138.8  699.26   166.6  690.53   174.5   688.6   190.4   687.2
   210.2  687.62   222.1  687.12     230  685.24     234  683.12   237.9  682.08
   253.8  681.88   257.8  681.96   266.1  683.56   273.6  685.74   285.5  686.81
   309.3  685.81   325.2  685.97   333.1  687.37     349  688.32   364.8  690.69
   384.7   692.7   400.5  691.51   416.1  694.56   467.1  697.23   482.7  699.59
#Mann= 3 ,-1 , 0
       0     .12       0     234    .045       0   266.1     .12       0
#XS Ineff= 2 , 0
                          290.12           688.1
Permanent Ineff=
       F       F
Bank Sta=234,266.1
XS Rating Curve= 0 ,0
Exp/Cntr=0.3,0.1

Type RM Length L Ch R = 1 ,12206.1 ,500.4,505.1,508.5
XS GIS Cut Line= 5
      2341713.39      391253.872      2341874.79      391149.929
     2341891.787      391147.432     2342115.734      390994.758
      2342182.14      390994.758
#Sta/Elev= 30
       0  727.11      28  720.87      44  718.65      64  713.92      84  708.38
     108  699.32     116  695.21     132  685.89     136  683.92     140  682.89
     148  682.51     172  683.86     189  679.64   198.8   678.9   213.1  679.48
   225.1   682.6   229.1  683.06     257  682.67   276.9  683.02   284.9  682.58
   296.8  683.57   328.7  682.83   368.6  687.66   376.6  690.29   388.5  695.51
   432.4  719.53   464.2  734.02   484.1  741.31   507.5  748.67   546.6  759.13
#Mann= 3 ,-1 , 0
       0     .12       0     189    .045       0   213.1     .12       0
Bank Sta=189,213.1
XS Rating Curve= 0 ,0
Exp/Cntr=0.3,0.1