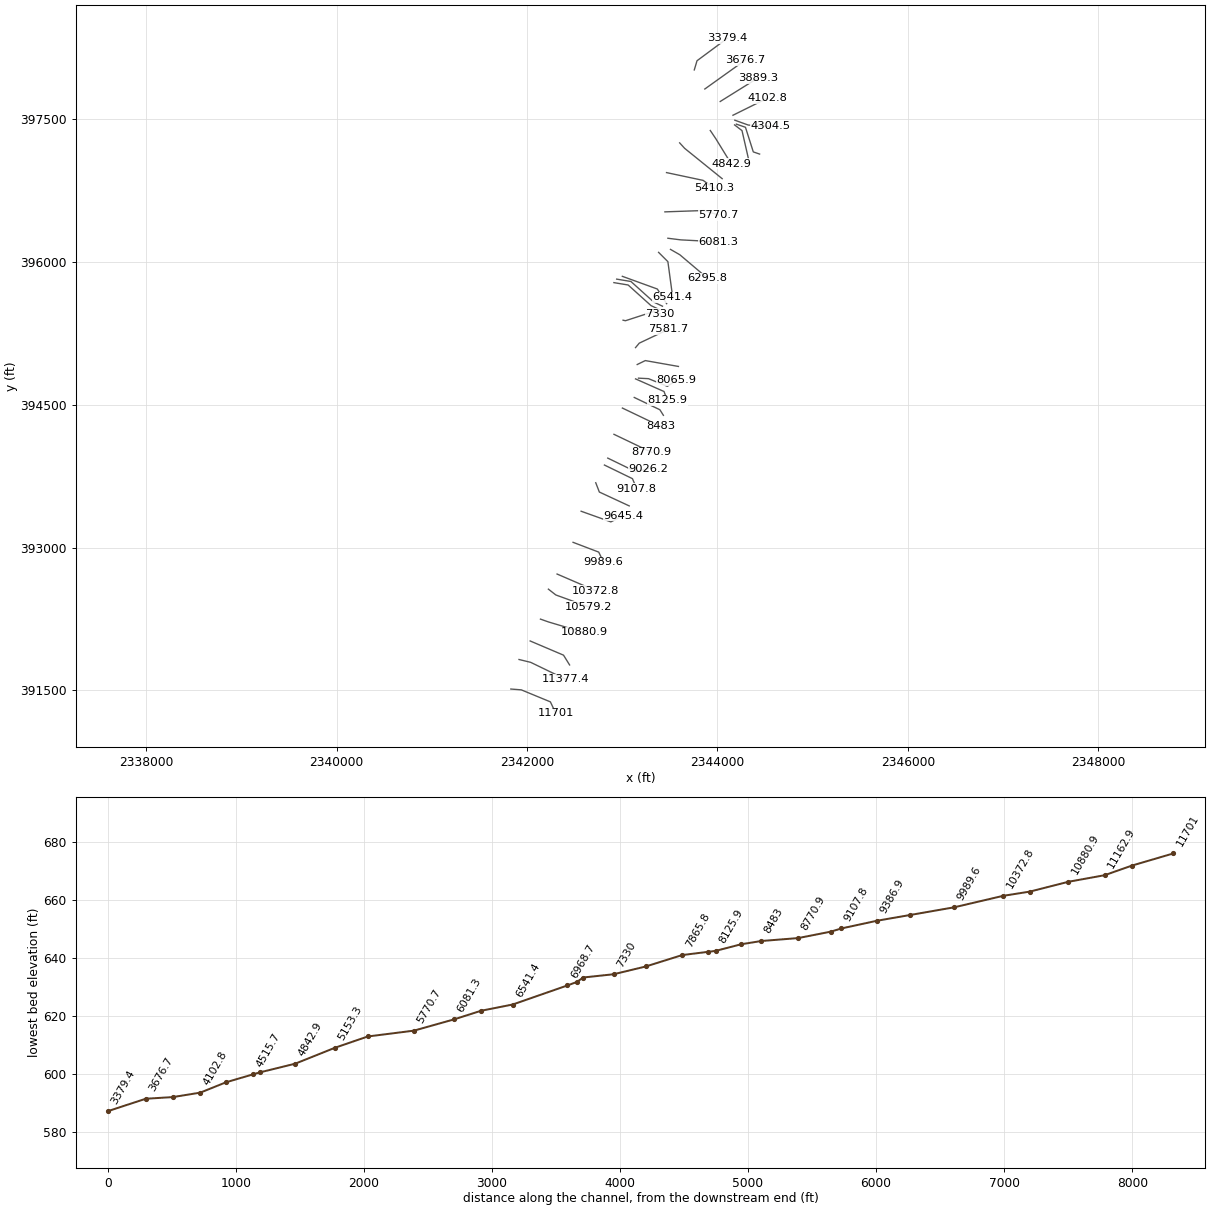
HEC-RAS study MOUNTAINRN.prj: MOUNTAINRN

--- MOUNTAINRN.g01 (geometry) --- (continued)

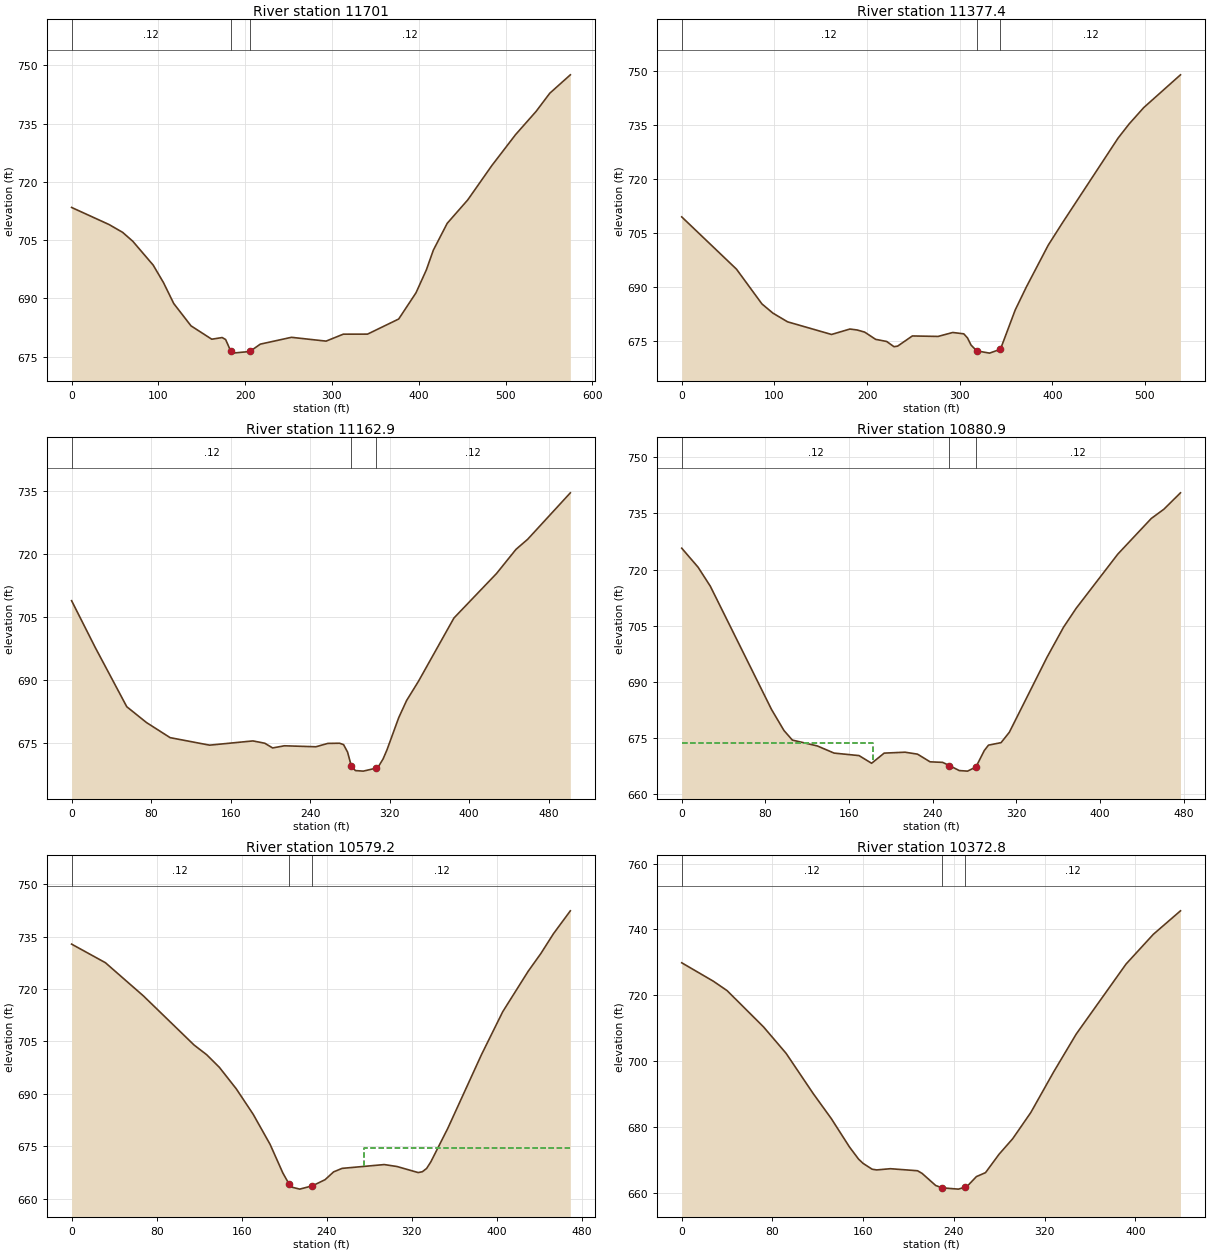
Type RM Length L Ch R = 1 ,11701   ,326.1,323.6,321.1
XS GIS Cut Line= 4
     2341830.589      391512.363     2341939.953      391503.872
     2342245.942       391377.57     2342303.234      391256.477
#Sta/Elev= 30
       0  713.41    43.1  709.02    58.8     707    70.5  704.71      94  698.57
   105.8   694.1   117.7  688.68   137.6  682.93   161.5  679.49   173.5  679.92
   177.5  679.41   183.1  676.56   185.5  675.91   205.4  676.33   217.4  678.22
   253.3  679.98   293.2     679   313.1  680.79     341   680.8   376.9  684.69
   396.8  691.42   408.8  697.34   416.8   702.4   432.8  709.32   456.5  715.36
   484.1  724.15   511.6  732.16   535.3  738.15     551  742.81   574.7  747.55
#Mann= 3 ,-1 , 0
       0     .12       0   183.1    .045       0   205.4     .12       0
Bank Sta=183.1,205.4
XS Rating Curve= 0 ,0
Exp/Cntr=0.3,0.1

Type RM Length L Ch R = 1 ,11377.4 ,213.2,214.5,215.7
XS GIS Cut Line= 3
     2341916.515      391822.883     2342038.911      391792.935
     2342410.005      391613.247
#Sta/Elev= 30
       0  709.48    59.1  694.99    86.6  685.35    98.4  682.81   114.2   680.4
   161.7  676.89   181.5   678.4   189.4  678.13   197.4  677.55   209.3  675.54
   221.2  674.95   229.1   673.5     233  673.66   248.9  676.48   276.7  676.35
   292.5  677.44   304.4  677.07   308.4  675.94   312.3  673.94   318.4  672.35
   332.2  671.72     344   672.8   359.9  683.66   371.8  689.98   395.6  701.66
   411.4  708.03   470.9   731.3   482.8  735.22   498.7  739.79   538.3  748.86
#Mann= 3 ,-1 , 0
       0     .12       0   318.4    .045       0     344     .12       0
Bank Sta=318.4,344
XS Rating Curve= 0 ,0
Exp/Cntr=0.3,0.1

Type RM Length L Ch R = 1 ,11162.9 ,279.2,282,284.8
XS GIS Cut Line= 3
     2342033.714      392017.571     2342383.963      391868.456
     2342447.765      391765.591
#Sta/Elev= 30
       0  708.95    23.8  697.81    55.5  683.72    75.3  679.96    99.1  676.36
   138.8  674.57   182.4  675.58   194.3  675.03   202.2  673.91   214.1  674.42
   245.8  674.19   257.8  674.99   269.6  675.03   273.6  674.69   277.6  672.92
   281.5  669.51   285.5  668.52   293.4  668.39   306.5  669.11   309.3  669.72
   313.3  671.28   317.2  673.42   329.1  681.14     337   685.2     349   689.8
   384.6  704.83   427.5  715.44     447  721.17   458.8  723.58   501.7  734.63
#Mann= 3 ,-1 , 0
       0     .12       0   281.5    .045       0   306.5     .12       0
Bank Sta=281.5,306.5
XS Rating Curve= 0 ,0
Exp/Cntr=0.3,0.1

Type RM Length L Ch R = 1 ,10880.9 ,303,301.7,300.3
XS GIS Cut Line= 3
     2342141.776      392247.362     2342226.411      392217.414
     2342597.505      392106.737
#Sta/Elev= 30
       0  725.72    15.6  720.65    27.3  715.58    85.9   682.6    97.8  676.98
   105.8  674.43   129.7  672.86   145.7  670.95   169.6  670.28   181.6  668.23
   193.6  670.94   213.5  671.19   225.5  670.67   237.5  668.62   249.5  668.47
     256  667.62   265.4  666.28   273.4  666.13   281.4  667.24   289.4  671.65
   293.4  673.08   305.4  673.74   313.3  676.51   349.3  696.54   365.2  704.62
   377.2  709.64   417.1  724.15   449.1  733.67   461.1  736.13     477  740.52
#Mann= 3 ,-1 , 0
       0     .12       0     256    .045       0   281.4     .12       0
#XS Ineff= 2 , 0
          182.93  673.55
Permanent Ineff=
       F       F
Bank Sta=256,281.4
XS Rating Curve= 0 ,0
Exp/Cntr=0.3,0.1

Type RM Length L Ch R = 1 ,10579.2 ,208.1,206.4,204.7
XS GIS Cut Line= 3
     2342225.109      392562.466     2342303.234      392501.268
      2342650.89      392374.966
#Sta/Elev= 30
       0  732.87    31.8  727.55    67.5  718.06   115.2  703.99   127.1   701.2
     139   697.6   154.9  691.44   170.8  684.16   186.7  675.55   198.7  667.36
   204.4  664.27   206.6  663.35   214.6  662.74   226.5  663.69   238.4  665.44
   246.4  667.67   254.4  668.68   294.1  669.77   306.1  669.21     326  667.48
   329.9  667.72   333.9  668.65   337.9  670.56   353.8  680.12   385.6  701.29
   405.5  713.52   429.4  725.08   441.3  730.15   453.2  735.84   469.1   742.4
#Mann= 3 ,-1 , 0
       0     .12       0   204.4    .045       0   226.5     .12       0
#XS Ineff= 2 , 0
                          274.71          674.41
Permanent Ineff=
       F       F
Bank Sta=204.4,226.5
XS Rating Curve= 0 ,0
Exp/Cntr=0.3,0.1

Type RM Length L Ch R = 1 ,10372.8 ,382.1,383.2,384.2
XS GIS Cut Line= 2
     2342316.255       392721.32     2342719.901      392546.841
#Sta/Elev= 30
       0  729.91      28   724.3      40  721.47      72  710.52      92  702.47
   115.9  690.27   131.9  682.66   147.9  674.07   155.9   670.4   159.9   669.1
   167.9  667.33   171.9  667.12   183.9  667.49   207.9  666.87   211.9  666.07
   223.9   662.4   229.6  661.69   243.9   661.3   249.6  661.88   251.8  662.22
   259.8   665.1   267.8  666.29   279.8  671.89   291.8  676.59   307.8  684.55
   327.8  696.78   347.8  708.31   391.8  729.56   415.8  738.55   439.7  745.66
#Mann= 3 ,-1 , 0
       0     .12       0   229.6    .045       0   249.6     .12       0
Bank Sta=229.6,249.6
XS Rating Curve= 0 ,0
Exp/Cntr=0.3,0.1

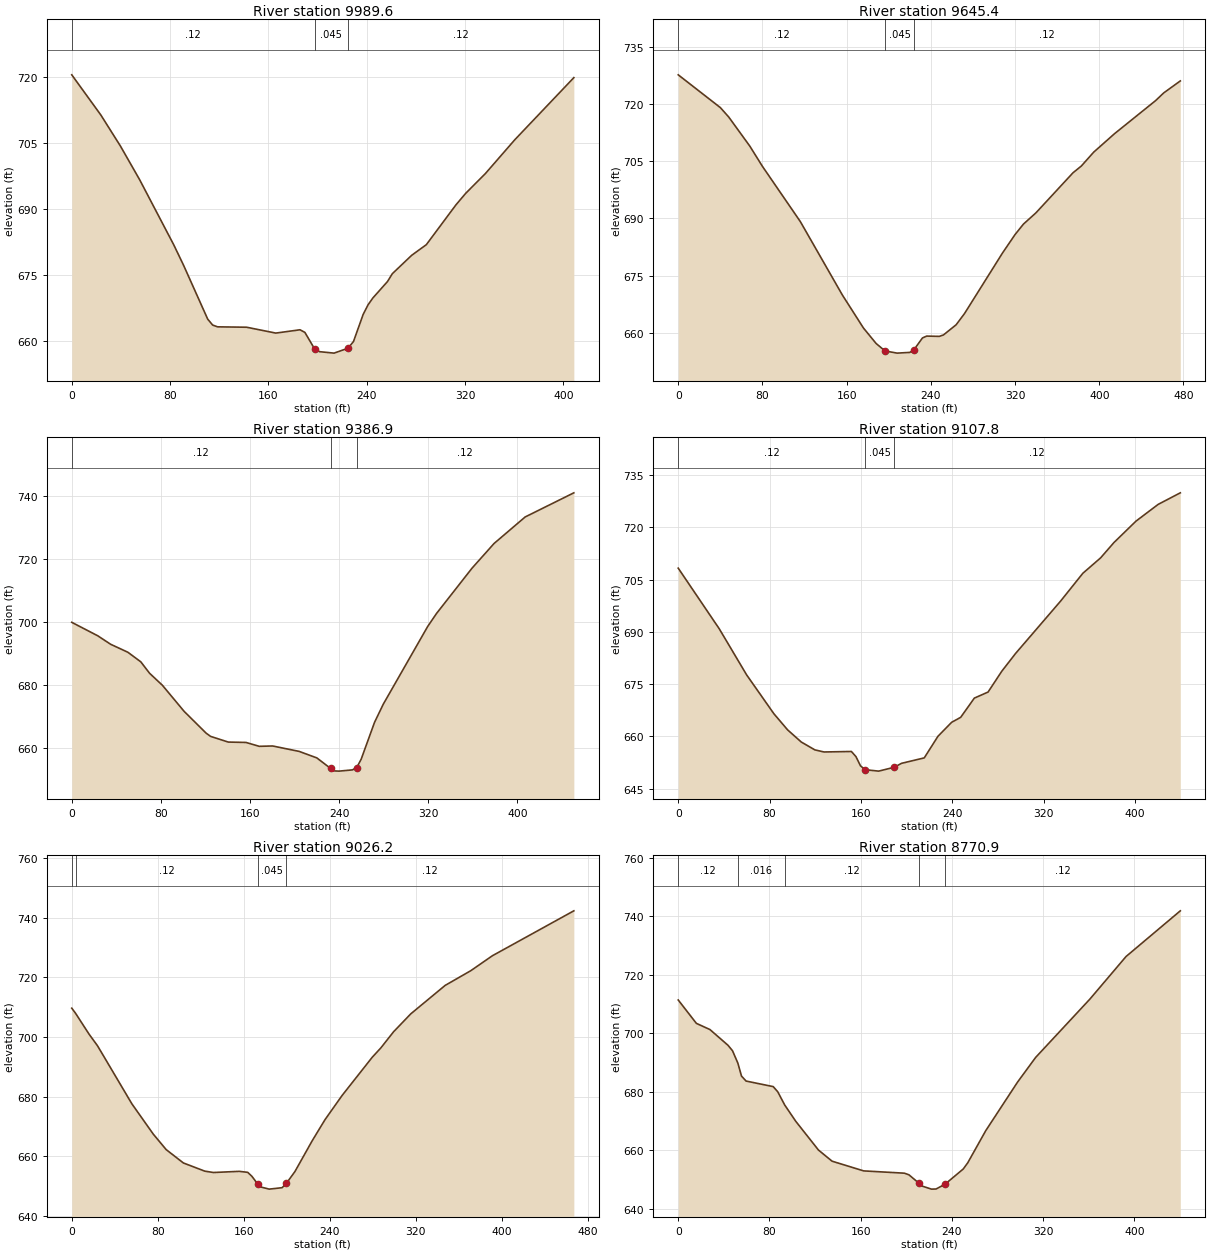
Type RM Length L Ch R = 1 ,9989.6  ,343.9,344.2,344.8
XS GIS Cut Line= 3
     2342484.224      393054.654     2342753.755      392951.789
     2342805.838      392843.716
#Sta/Elev= 30
       0  720.53    23.7  711.39    39.5   704.4    55.3  696.68      83  681.92
    90.9  677.33   110.6  665.06   114.6  663.72   118.6  663.31   142.3  663.22
     166  661.89   185.7  662.64   189.7  662.04   197.6  658.28   201.6  657.67
   213.4  657.34   224.7  658.45   229.2  659.97   237.1  666.14   241.1  668.32
     245  669.87   256.9   673.6   260.8  675.37   276.6  679.56   288.5  681.97
   312.5  690.98   320.5  693.62   336.5   698.1   360.5   705.8   408.5  719.89
#Mann= 3 ,-1 , 0
       0     .12       0   197.6    .045       0   224.7     .12       0
Bank Sta=197.6,224.7
XS Rating Curve= 0 ,0
Exp/Cntr=0.3,0.1

Type RM Length L Ch R = 1 ,9645.4  ,260.7,258.5,256
XS GIS Cut Line= 3
     2342568.859      393381.477     2342881.359      393269.497
     2343010.265      393335.904
#Sta/Elev= 30
       0  727.66      40  719.07      48  716.59      68  708.97      80  703.66
     116  689.18     156   669.9     176  661.26     188  657.22   196.4  655.27
     208  654.69     220  654.88     224  655.59     232  658.66     236  659.16
     248  659.08     252  659.46     264  662.12     272  665.07     308  680.91
     320  685.78     328  688.53   339.8  691.46   375.1  701.99   382.9  703.73
   394.7  707.38   414.3  712.18   453.4  720.87   461.3  722.93     477  726.06
#Mann= 3 ,-1 , 0
       0     .12       0   196.4    .045       0     224     .12       0
Bank Sta=196.4,224
XS Rating Curve= 0 ,0
Exp/Cntr=0.3,0.1

Type RM Length L Ch R = 1 ,9386.9  ,279.6,279.1,278.7
XS GIS Cut Line= 3
     2342722.505      393680.956     2342760.265      393583.299
     2343074.067      393437.466
#Sta/Elev= 30
       0  699.98    23.3  695.71    34.9  693.01    50.4  690.47      62  687.42
    69.8  683.82    81.4  679.97   100.8  671.72   120.6  664.78   124.6  663.75
   140.5  661.94   156.4  661.82   168.3  660.59   180.3   660.7   204.1  658.98
     220  656.91   232.4  653.55     236  652.77   239.9  652.71   251.9   653.1
   255.8  653.83   259.8   656.5   271.8  668.22   279.7  674.02   319.5  698.66
   327.4  702.78   359.3  717.18   379.1  725.03     407  733.45   450.7  741.12
#Mann= 3 ,-1 , 0
       0     .12       0   232.4    .045       0   255.8     .12       0
Bank Sta=232.4,255.8
XS Rating Curve= 0 ,0
Exp/Cntr=0.3,0.1

Type RM Length L Ch R = 1 ,9107.8  ,81.6,81.6,81.6
XS GIS Cut Line= 3
     2342813.651      393867.154     2343107.921      393723.924
     2343152.203      393620.436
#Sta/Elev= 30
       0  708.31    35.9  690.92    59.9  677.68    83.8  666.51    95.8  661.89
   107.8  658.39   119.7  656.14   127.7  655.54   151.7  655.68   155.7  654.19
   159.6  651.59   163.6  650.45   175.6  650.04   189.2  651.15   195.6  652.28
   215.5  653.84   227.5  660.04   239.5  664.06   247.4  665.48   259.4  671.01
   271.4  672.74   283.4  678.71   295.4  683.78     335  698.88   354.4  706.83
     370  711.27   381.6  715.64     401  721.82   420.4  726.62   439.8  729.94
#Mann= 3 ,-1 , 0
       0     .12       0   163.6    .045       0   189.2     .12       0
Bank Sta=163.6,189.2
XS Rating Curve= 0 ,0
Exp/Cntr=0.3,0.1

Type RM Length L Ch R = 1 ,9026.2  ,255.2,255.3,255.5
XS GIS Cut Line= 3
     2342848.807       393940.07     2343143.078      393796.841
     2343278.494      393830.695
#Sta/Elev= 30
       0  709.61    3.55707.8882      16  700.95      24  696.98    55.9  677.55
    75.8  667.39    87.8   662.2   103.8  657.72   123.7  654.98   131.7  654.52
   155.7  654.91   163.6  654.58   167.6  653.22   173.2  650.51   175.6  649.68
   183.6  648.95   195.6  649.43   199.6  650.89   207.5  654.83   223.5  665.11
   235.5  672.24   251.4  680.35   279.4  693.15   287.4  696.28   299.3  701.72
   315.3  707.72   347.2  717.24   371.2  722.21   391.1  727.18   466.9  742.25
#Mann= 4 ,-1 , 0
       0    .016       0    3.55     .12       0   173.2    .045       0
   199.6     .12       0
Bank Sta=173.2,199.6
XS Rating Curve= 0 ,0
Exp/Cntr=0.3,0.1

Type RM Length L Ch R = 1 ,8770.9  ,287.9,287.9,287.9
XS GIS Cut Line= 2
     2342913.911       394190.07     2343311.046      393999.966
#Sta/Elev= 30
       0  711.36    15.9  703.38    27.8  701.26    43.6   695.9    47.6  694.02
   52.29689.7864    55.5  685.35    59.5  683.66    83.3  681.76    87.3  679.98
   93.31675.5227   103.1  669.89     123  660.08   134.9  656.28   162.6  652.96
   198.3  652.18   202.3  651.63   210.8  648.85   214.2  647.73   222.1  646.73
   226.1  646.77     234  648.42   249.9  653.59   253.9  655.73   269.7  666.72
   297.5  683.26   313.4  691.72     361  711.66   392.7  726.21   440.3  741.83
#Mann= 5 ,-1 , 0
       0     .12       0   52.29    .016       0   93.31     .12       0
   210.8    .045       0     234     .12       0
Bank Sta=210.8,234
XS Rating Curve= 0 ,0
Exp/Cntr=0.3,0.1

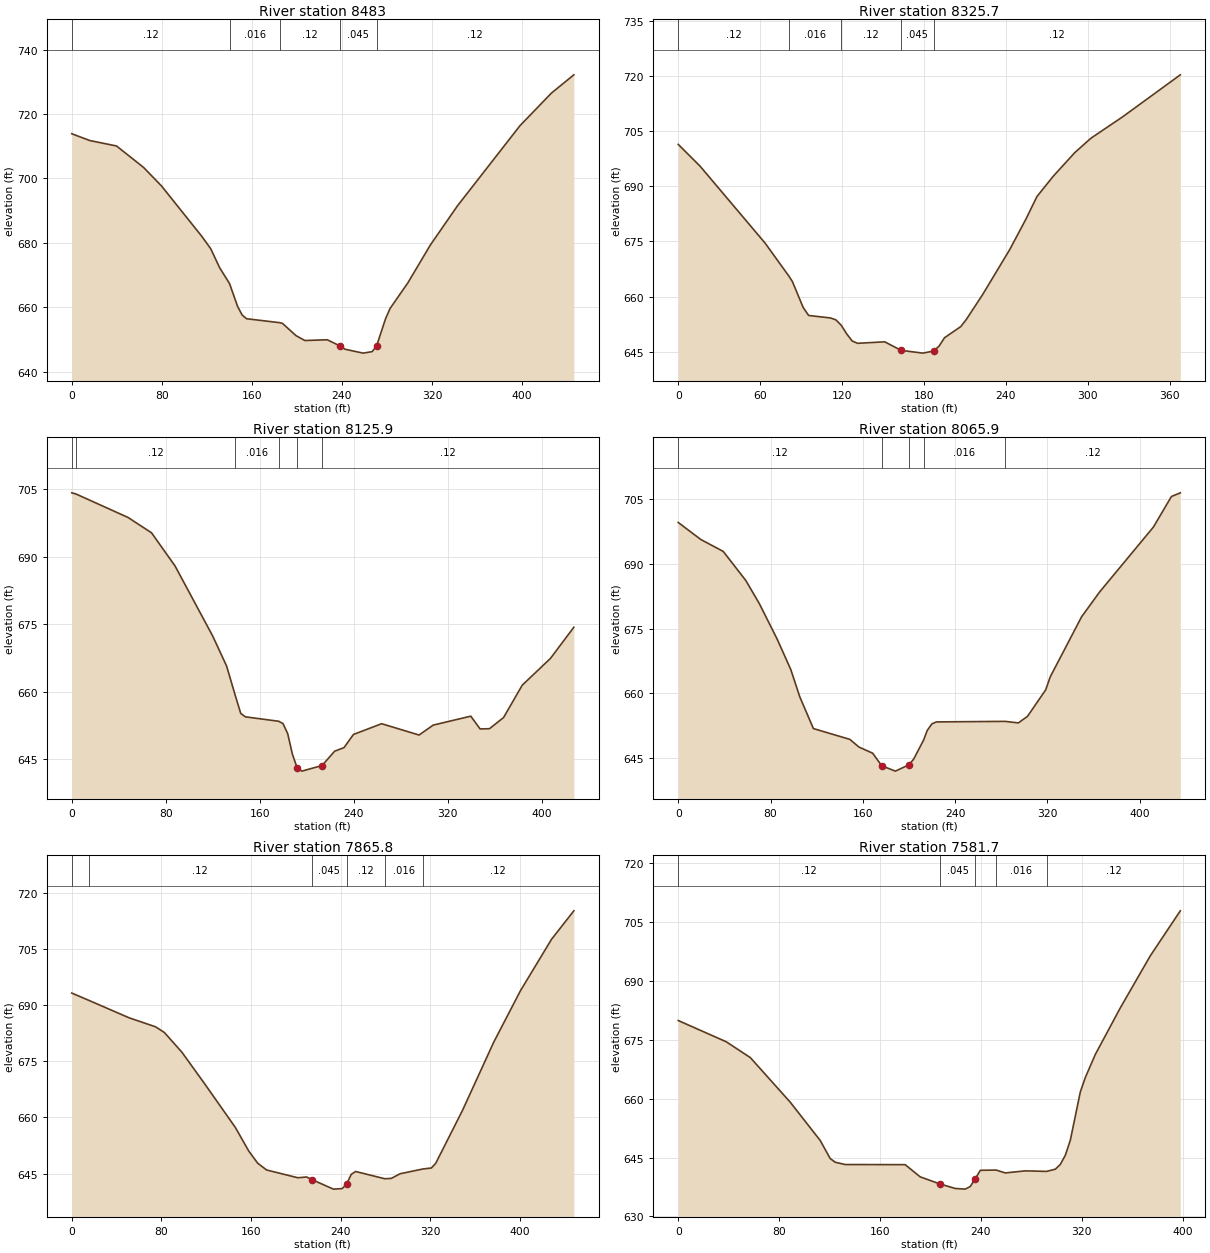
Type RM Length L Ch R = 1 ,8483    ,157.9,157.3,156.7
XS GIS Cut Line= 2
     2343002.453      394466.112     2343404.796      394273.404
#Sta/Elev= 30
       0   713.9    15.9   711.8    39.8  710.09    63.7  703.46    79.7  697.69
   115.5  682.03   123.5  678.15   131.4  672.26  140.19667.3367   147.4  660.19
   151.4  657.56   155.3  656.41  184.71655.1816   187.2  654.97   199.2  651.17
   207.1  649.64     227  649.87   238.1     648     243  646.91   258.9  645.72
   266.9  646.19   270.8  647.92   278.8   656.4   282.8  659.59   298.7   667.6
   318.6  679.32   342.6  691.45   398.3  716.43   426.2  726.54   446.1  732.21
#Mann= 5 ,-1 , 0
       0     .12       0  140.19    .016       0  184.71     .12       0
   238.1    .045       0   270.8     .12       0
Bank Sta=238.1,270.8
XS Rating Curve= 0 ,0
Exp/Cntr=0.3,0.1

Type RM Length L Ch R = 1 ,8325.7  ,198.5,199.8,201
XS GIS Cut Line= 3
     2343127.051      394577.588     2343396.148      394448.465
     2343433.041      394389.871
#Sta/Elev= 30
       0  701.42    15.9  695.53    63.7  674.51   81.08 665.539    83.6  664.09
    91.5  657.03    95.5  654.85   111.4  654.18   115.4  653.67   119.3 652.227
   123.4  649.83   127.4   647.9   131.3  647.27   151.2  647.68   163.2  645.36
   179.1   644.6     187  645.17     191  646.49     195  648.78   206.9  651.82
   210.9  653.72   222.9  660.52   242.8   672.8   254.7  681.12   262.7  687.22
   274.6  692.73   290.5  699.21   302.3  703.11   325.4   708.9   367.7  720.35
#Mann= 5 ,-1 , 0
       0     .12       0   81.08    .016       0   119.3     .12       0
   163.2    .045       0     187     .12       0
Bank Sta=163.2,187
XS Rating Curve= 0 ,0
Exp/Cntr=0.3,0.1

Type RM Length L Ch R = 1 ,8125.9  ,59.2,60,60.7
XS GIS Cut Line= 3
     2343140.474      394772.753     2343439.953       394639.94
     2343473.807       394546.19
#Sta/Elev= 30
       0  704.23    3.37703.9941    47.9  698.75    67.9  695.33    87.9  687.96
   119.9  672.39   131.8  665.68  139.01659.2675   143.8  655.16   147.8  654.39
  176.13 653.403   179.8  652.88   183.8  650.64   187.8  646.05   191.8  643.07
   195.8  642.31     213  643.55   223.7  646.74   231.7  647.54   239.7  650.46
   263.7  652.86   295.6  650.34   307.6  652.55   339.6  654.54   347.5   651.7
   355.5  651.75   367.5  654.24   383.4  661.44   407.4  667.39   427.3  674.32
#Mann= 6 ,-1 , 0
       0     .06       0    3.37     .12       0  139.01    .016       0
  176.13     .12       0   191.8    .045       0     213     .12       0
Bank Sta=191.8,213
XS Rating Curve= 0 ,0
Exp/Cntr=0.3,0.1

Type RM Length L Ch R = 1 ,8065.9  ,195.1,200.1,205.5
XS GIS Cut Line= 4
     2343171.539      394780.496     2343276.791      394775.071
     2343474.273      394694.776      2343571.93      394758.795
#Sta/Elev= 30
       0  699.64    19.5   695.7      39  692.93    58.6  686.18    70.3  680.83
    85.9  672.52    97.6  665.53   105.4   659.2   117.2  651.85   148.8  649.34
   156.7  647.56   168.6  646.13   176.4  643.23   188.3  641.98   200.1  643.46
   204.1  644.76  212.69649.1647   215.9  651.42   219.9  652.93   223.8  653.39
  283.32 653.518   294.9  653.16   302.8  654.68   318.6  660.83   322.5  663.82
   349.7  677.76   365.3  683.51     412  698.58   427.6  705.66   435.3  706.51
#Mann= 5 ,-1 , 0
       0     .12       0   176.4    .045       0   200.1     .12       0
  212.69    .016       0  283.32     .12       0
Bank Sta=176.4,200.1
XS Rating Curve= 0 ,0
Exp/Cntr=0.3,0.1

Type RM Length L Ch R = 1 ,7865.8  ,269,284.1,298.7
XS GIS Cut Line= 3
     2343158.094      394923.772     2343242.883      394965.186
     2343590.994      394903.612
#Sta/Elev= 30
       0   693.2   15.01691.2791    51.1   686.6    74.7   684.2    82.6  682.68
    98.3   677.4   118.2  669.14     146  657.31   157.9  651.04   165.9  647.79
   173.8  645.99   201.6  643.92   209.6  644.11   214.1  643.44   233.4  640.88
   241.3  641.02   245.3  642.31   249.3  644.81   253.2  645.59  279.16643.6529
     285  643.74     293  644.99  313.17646.2482   320.8  646.52   324.7  647.78
   348.6  661.91   376.4  680.07   400.2  693.78     428  707.55   447.9  715.14
#Mann= 6 ,-1 , 0
       0     .06       0   15.01     .12       0   214.1    .045       0
   245.3     .12       0  279.16    .016       0  313.17     .12       0
Bank Sta=214.1,245.3
XS Rating Curve= 0 ,0
Exp/Cntr=0.3,0.1

Type RM Length L Ch R = 1 ,7581.7  ,255.1,251.7,248.3
XS GIS Cut Line= 3
     2343140.474      395101.529     2343179.536      395148.404
     2343484.224      395292.935
#Sta/Elev= 30
       0  679.94    38.1  674.52    57.2  670.48    88.8  659.13   112.6  649.36
   120.5  644.76   124.5  643.81   132.4  643.22     180  643.19   191.9  640.08
   207.8  638.24   219.7  637.12   227.6  636.95   231.6  637.62   235.6   639.6
   239.6  641.75  252.15  641.81   259.4  641.08   275.3  641.61   292.1641.4675
   299.1  642.04     303  643.24     307  645.58     311  649.46   318.9  661.73
   322.9  665.44   330.8   671.3   350.6  683.16   374.4  696.44   398.2  707.91
#Mann= 5 ,-1 , 0
       0     .12       0   207.8    .045       0   235.6     .12       0
  252.15    .016       0   292.1     .12       0
Bank Sta=207.8,235.6
XS Rating Curve= 0 ,0
Exp/Cntr=0.3,0.1

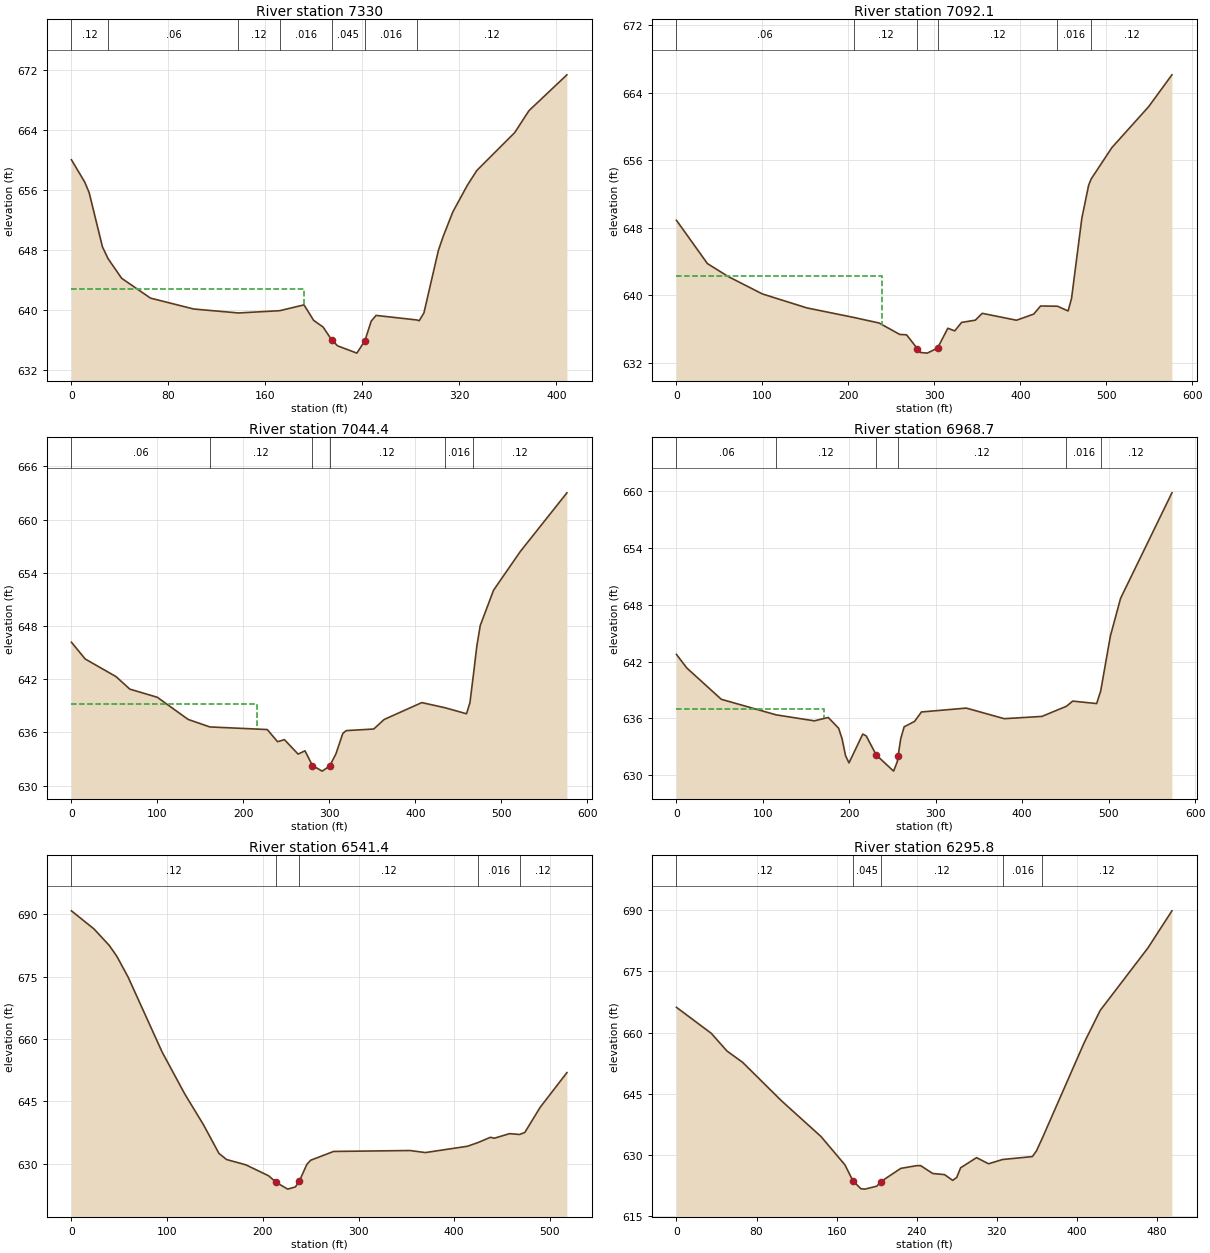
Type RM Length L Ch R = 1 ,7330    ,265,237.9,210.8
XS GIS Cut Line= 4
     2343009.592      395389.763     2343034.602      395384.175
     2343331.858      395480.909     2343398.047      395457.037
#Sta/Elev= 30
       0     660      11  657.02    14.6  655.63    25.6   648.4   30.26646.8288
    41.4  644.23    65.2  641.59   100.8  640.14  137.77639.6143  171.78639.9166
   191.8  640.69   199.7  638.64   207.6  637.73   214.5  636.06   219.5  635.24
   235.4  634.27  241.98  635.91   247.2  638.52   251.2  639.29  284.82 638.684
   286.8  638.58   290.7  639.63   302.6  647.93   306.6  649.81   314.5  653.05
   326.4  656.58   334.3  658.57   365.6  663.62   377.3  666.53   408.6   671.3
#Mann= 7 ,-1 , 0
       0     .12       0   30.26     .06       0  137.77     .12       0
  171.78    .016       0   214.5    .045       0  241.98    .016       0
  284.82     .12       0
#XS Ineff= 2 , 0
          191.91   642.8
Permanent Ineff=
       F       F
Bank Sta=214.5,241.98
XS Rating Curve= 0 ,0
Exp/Cntr=0.3,0.1

Type RM Length L Ch R = 1 ,7092.1  ,47,47.7,48.4
XS GIS Cut Line= 4
     2342913.021      395784.728     2343062.761      395759.772
     2343303.234      395542.935      2343394.38      395499.966
#Sta/Elev= 30
       0  648.89      36  643.76    59.9  642.24    99.9  640.16   151.8   638.5
  206.22637.3729   235.8  636.71   259.7  635.36   267.7  635.31   280.3  633.67
   283.7  633.22   291.7  633.14   303.7  633.74   315.7  636.09   323.7  635.78
   331.7  636.78   347.7  637.05   355.7  637.86   395.6  637.04   415.6  637.77
   423.6  638.73  443.27638.7015   455.6  638.14   459.6  639.62   471.6  649.14
   479.5  653.05  482.57653.8136   506.6  657.52   549.2  662.35   576.4  666.14
#Mann= 6 ,-1 , 0
       0     .06       0  206.22     .12       0   280.3    .045       0
   303.7     .12       0  443.27    .016       0  482.57     .12       0
#XS Ineff= 2 , 0
          239.54   642.3
Permanent Ineff=
       F       F
Bank Sta=280.3,303.7
XS Rating Curve= 0 ,0
Exp/Cntr=0.3,0.1

Type RM Length L Ch R = 1 ,7044.4  ,66.9,75.7,84.6
XS GIS Cut Line= 4
     2342942.318      395821.621     2343092.058      395796.664
     2343332.531      395579.827     2343423.677      395536.859
#Sta/Elev= 30
       0  646.17      16  644.28    51.9  642.29    67.9  640.88    99.9  639.96
   135.8  637.46  161.02636.6156   227.8  636.32   239.8  634.95   247.8  635.18
   263.7  633.55   271.7  633.92   280.4  632.26   291.7  631.63   300.4   632.2
   307.7  633.58   315.7  635.88   319.7   636.2   351.7  636.38   363.7  637.45
   407.6  639.36  434.64638.7796   459.6   638.1   463.6  639.35  467.72642.5674
   471.6  645.72   475.6  648.06   491.1  652.04   522.1  656.39   576.4  663.02
#Mann= 6 ,-1 , 0
       0     .06       0  161.02     .12       0   280.4    .045       0
   300.4     .12       0  434.64    .016       0  467.72     .12       0
#XS Ineff= 2 , 0
          216.43   639.2
Permanent Ineff=
       F       F
Bank Sta=280.4,300.4
XS Rating Curve= 0 ,0
Exp/Cntr=0.3,0.1

Type RM Length L Ch R = 1 ,6968.7  ,454.1,427.2,400.3
XS GIS Cut Line= 3
     2343001.997      395850.917      2343369.64      395717.414
     2343467.296      395563.768
#Sta/Elev= 30
       0  642.75      12  641.31    51.9     638  115.42636.3528   159.6  635.72
   175.6  636.08   187.6  634.94   191.6  633.82   195.6  632.04   199.6  631.27
   215.5  634.32   219.5  634.13   231.2   632.1   251.2   630.4   255.4  631.38
  256.48  632.03   259.4  633.81   263.4  635.09   275.4  635.66   283.4  636.66
   335.3  637.07   379.2  635.95   422.8  636.19  451.12637.2617   458.4  637.81
   486.1  637.55  490.78638.8766     502   644.7   513.8  648.69   573.2  659.85
#Mann= 6 ,-1 , 0
       0     .06       0  115.42     .12       0   231.2    .045       0
  256.48     .12       0  451.12    .016       0  490.78     .12       0
#XS Ineff= 2 , 0
          170.99  636.93
Permanent Ineff=
       F       F
Bank Sta=231.2,256.48
XS Rating Curve= 0 ,0
Exp/Cntr=0.3,0.1

Type RM Length L Ch R = 1 ,6541.4  ,227.3,245.6,263.5
XS GIS Cut Line= 3
     2343382.661      396102.831     2343480.317      396005.174
     2343531.099      395628.872
#Sta/Elev= 30
       0  690.88    23.7  686.49    39.5  682.55    47.4  679.95    59.2  674.93
    94.7   656.9   118.4  646.77   138.1   639.3   154.1  632.46   162.1  630.96
   182.1   629.7   206.1  627.04   214.2  625.43     226  623.83     234  624.35
     238  625.67     246  629.78     250  630.79     274  632.91   353.9  633.13
   369.9  632.64   413.9  634.16  424.77635.0413   437.9  636.32   441.9  636.09
   457.9   637.2  468.42636.9955   473.8  637.48   489.8  643.52   517.8   651.9
#Mann= 5 ,-1 , 0
       0     .12       0   214.2    .045       0     238     .12       0
  424.77    .016       0  468.42     .12       0
Bank Sta=214.2,238
XS Rating Curve= 0 ,0
Exp/Cntr=0.3,0.1

Type RM Length L Ch R = 1 ,6295.8  ,197.6,214.5,231.5
XS GIS Cut Line= 3
     2343507.661      396134.081     2343605.317      396078.091
     2343896.984      395830.695
#Sta/Elev= 30
       0  666.21    34.9  659.82    50.5   655.5      66  652.76   104.8  643.35
   144.4  634.57   168.3  627.64   176.3  623.72   184.3  621.78   188.3  621.69
   200.2  622.42   204.2  623.52   224.1  626.77     240  627.44     244  627.44
     256  625.52   267.9  625.24   275.9  623.84   279.9  624.52   283.9  626.92
   299.8   629.4   311.8   627.9  325.81628.9444   355.6  629.66   359.6  631.04
   365.6634.2246   407.4  657.59   423.3  665.44   471.1  680.78     495  689.84
#Mann= 5 ,-1 , 0
       0     .12       0   176.3    .045       0   204.2     .12       0
  325.81    .016       0   365.6     .12       0
Bank Sta=176.3,204.2
XS Rating Curve= 0 ,0
Exp/Cntr=0.3,0.1

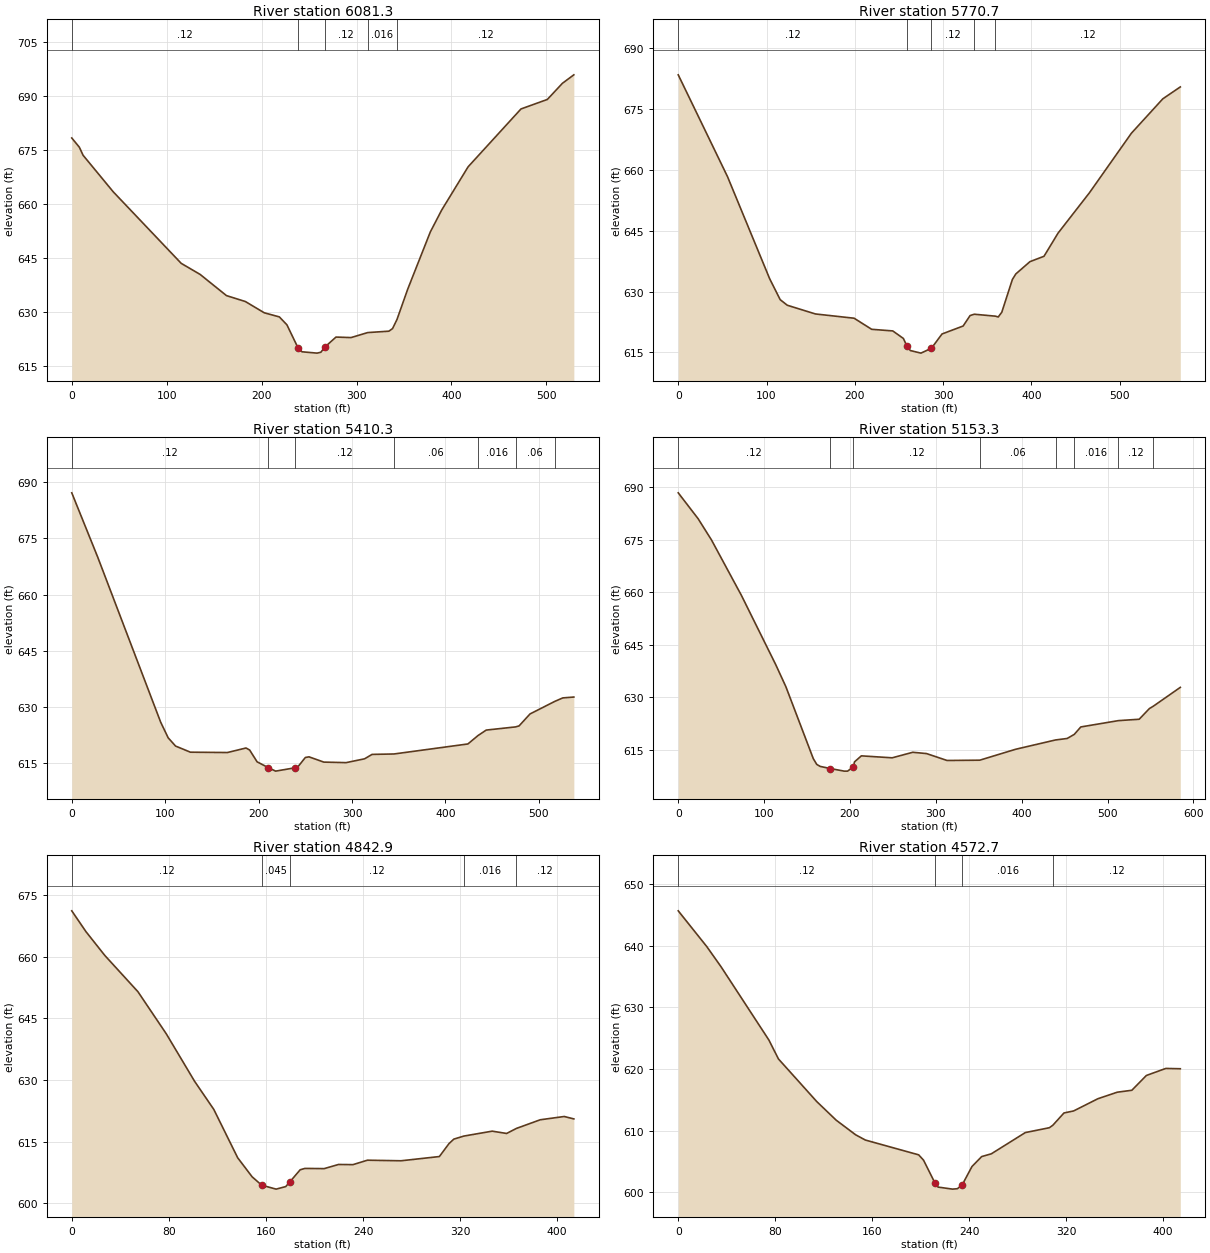
Type RM Length L Ch R = 1 ,6081.3  ,308.5,310.6,312.9
XS GIS Cut Line= 3
     2343480.317      396251.268     2343614.432      396234.341
     2344007.661      396213.508
#Sta/Elev= 30
       0   678.3       8  675.74    11.9  673.52    43.7  663.38   115.3  643.56
   135.2   640.5     163  634.62   182.9  632.98   202.8  629.86   218.7  628.72
   226.7  626.52   238.6  620.03   242.6  619.05   258.5  618.68   262.5  618.93
   266.4   620.3   278.4  623.13   294.3  622.99  311.81624.3735   334.1  624.76
     338  625.48  342.67628.0123     354  636.42   377.8  652.27   389.7   658.3
   417.6  670.31   473.3  686.34   501.1  688.98     517  693.46     529   695.8
#Mann= 5 ,-1 , 0
       0     .12       0   238.6    .045       0   266.4     .12       0
  311.81    .016       0  342.67     .12       0
Bank Sta=238.6,266.4
XS Rating Curve= 0 ,0
Exp/Cntr=0.3,0.1

Type RM Length L Ch R = 1 ,5770.7  ,366.5,360.4,354.3
XS GIS Cut Line= 3
     2343449.067      396528.612      2343863.13      396542.935
     2344010.265       396496.06
#Sta/Elev= 30
       0   683.4    55.8  658.32   103.6  633.14   115.5     628   123.5  626.63
   155.4  624.48   199.2  623.43   219.1   620.7     243   620.3     255  618.45
   258.9  616.64   262.9  615.47   274.9  614.83   286.8  616.03   298.8  619.55
   322.7  621.51   330.6  624.09   335.3624.4123  359.16623.9404   362.5  623.74
   366.5  624.91   378.5  632.98   382.4  634.34   398.4  637.37   414.3  638.69
   430.2  644.39   465.8  654.35   513.3  669.01   548.9  677.49   568.7  680.42
#Mann= 5 ,-1 , 0
       0     .12       0   258.9    .045       0   286.8     .12       0
   335.3    .016       0  359.16     .12       0
Bank Sta=258.9,286.8
XS Rating Curve= 0 ,0
Exp/Cntr=0.3,0.1

Type RM Length L Ch R = 1 ,5410.3  ,269.3,257,244.6
XS GIS Cut Line= 3
     2343465.994      396941.372     2343850.217      396859.753
     2343967.405      396775.118
#Sta/Elev= 30
       0   687.2    27.8     670    95.2  625.88   103.2  621.72   111.1  619.52
     127  617.88   166.6  617.79   186.5     619   190.4  618.46   198.4   615.3
   210.3  613.76   218.2  612.82   239.4  613.73     242  613.96     250  616.46
   253.9  616.64   269.8  615.23   293.6  615.09   313.4  616.11   321.4  617.29
  344.91617.4027     424  620.08   434.8622.3221   443.6  623.79  475.07624.6396
   478.8  624.91   490.5   628.1  517.13631.4734   525.6  632.39   537.4  632.62
#Mann= 7 ,-1 , 0
       0     .12       0   210.3    .045       0   239.4     .12       0
  344.91     .06       0   434.8    .016       0  475.07     .06       0
  517.13     .08       0
Bank Sta=210.3,239.4
XS Rating Curve= 0 ,0
Exp/Cntr=0.3,0.1

Type RM Length L Ch R = 1 ,5153.3  ,319,310.4,302
XS GIS Cut Line= 3
     2343604.015      397253.872     2343656.099      397196.581
      2344050.63       396877.57
#Sta/Elev= 30
       0  688.36    23.2  680.96    38.7  674.92    73.6  659.08   113.4   639.4
   125.4  633.01   157.3  612.49   161.3  610.85   165.3  610.27   177.3  609.65
   193.3  608.92   197.3  608.92  204.11   610.2   205.3  611.56   213.3  613.28
   249.2  612.72   273.2   614.3   289.2  613.93   313.1  611.96  351.21612.0422
     393  615.16  439.48617.8168     453  618.24  461.27619.4031   468.9  621.53
  512.61623.3313   536.9  623.73   548.8  626.78  553.35627.4525   584.8  632.83
#Mann= 8 ,-1 , 0
       0     .12       0   177.3    .045       0  204.11     .12       0
  351.21     .06       0  439.48     .12       0  461.27    .016       0
  512.61     .12       0  553.35     .06       0
Bank Sta=177.3,204.11
XS Rating Curve= 0 ,0
Exp/Cntr=0.3,0.1

Type RM Length L Ch R = 1 ,4842.9  ,278.4,270.2,261.8
XS GIS Cut Line= 3
      2343925.63      397384.081     2343984.224      397296.841
     2344145.682       397033.82
#Sta/Elev= 30
       0  671.17    11.7   666.1    27.2  660.32    54.5  651.49    77.8  641.27
   101.2  629.68     117  622.85   136.7  611.07   148.6  606.43   156.5  604.39
   168.4  603.43   176.3  604.05   179.7  605.19   188.2  608.14   192.1  608.47
     208  608.42   219.8  609.43   231.7  609.39   243.6  610.47   271.3  610.33
   302.9  611.36   310.8   614.5   314.8   615.6  323.04616.3431   346.4  617.54
   358.3  616.98  366.43618.2114     386  620.31   405.8  621.11   413.7  620.52
#Mann= 5 ,-1 , 0
       0     .12       0   156.5    .045       0   179.7     .12       0
  323.04    .016       0  366.43     .12       0
Bank Sta=156.5,179.7
XS Rating Curve= 0 ,0
Exp/Cntr=0.3,0.1

Type RM Length L Ch R = 1 ,4572.7  ,54.9,57,59
XS GIS Cut Line= 3
     2344180.838      397442.674     2344258.963      397382.779
     2344329.287      397074.863
#Sta/Elev= 30
       0  645.63    23.6  639.82    35.4  636.54    74.8  624.68    82.7  621.61
   114.4  614.68   130.4  611.67   146.4  609.31   154.4  608.46   198.4  606.06
   202.4   605.2   211.8  601.51   214.4  600.83   226.4   600.5   230.4  600.57
   234.4  601.22   242.4  604.17   250.4  605.78   258.4  606.23   286.4  609.67
   306.3  610.46  309.14610.8647   318.3  612.85   326.3  613.18   346.3  615.16
   362.3  616.22   374.3  616.53   386.3  618.93   402.3  620.07   414.3  620.02
#Mann= 4 ,-1 , 0
       0     .12       0   211.8    .045       0   234.4    .016       0
  309.14     .12       0
Bank Sta=211.8,234.4
XS Rating Curve= 0 ,0
Exp/Cntr=0.3,0.1

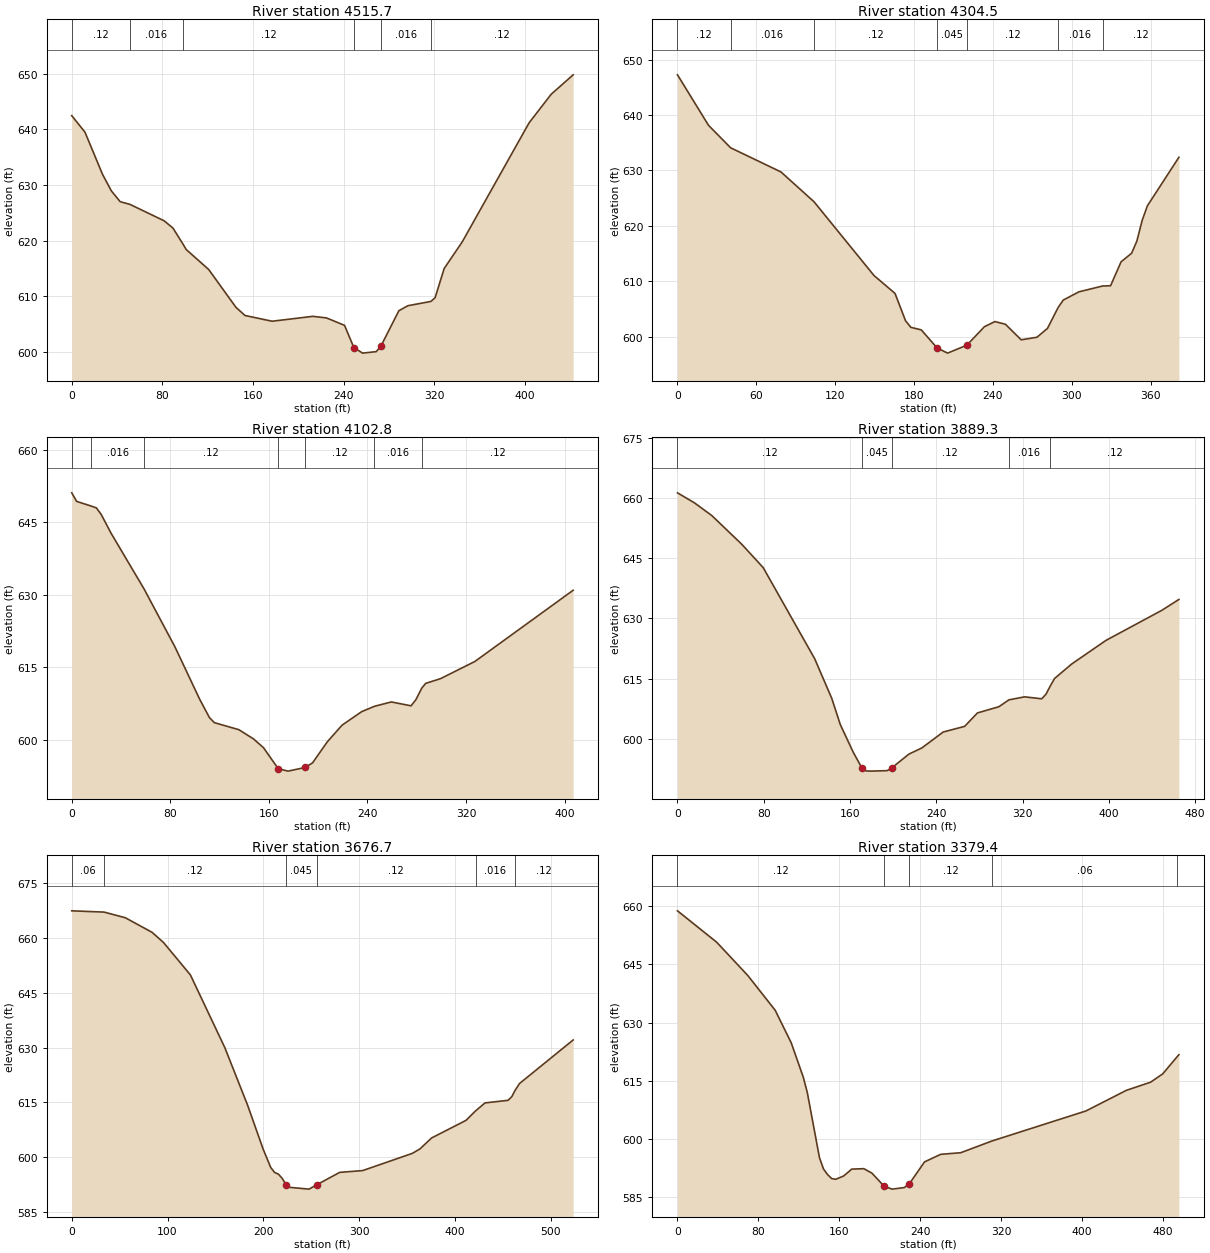
Type RM Length L Ch R = 1 ,4515.7  ,181.5,211.2,240.8
XS GIS Cut Line= 4
      2344199.61      397450.845     2344295.165       397417.92
     2344377.561      397158.961      2344443.75      397136.175
#Sta/Elev= 30
       0  642.44    11.7  639.47    27.2  631.89      35  628.92    42.8  626.98
   51.27626.5125    81.6  623.55    89.4  622.24   98.23619.3687   101.1  618.39
     121  614.79     145  608.01     153  606.54     177  605.51     213  606.39
     225   606.1   240.9  604.77   249.2  600.76   256.9  599.78   268.9  600.05
   272.9  600.99   288.9   607.4   296.9   608.3  317.14609.0632   320.9  609.74
   328.9  614.98   344.8  619.75   403.9  641.15   423.4  646.28   442.8  649.77
#Mann= 6 ,-1 , 0
       0     .12       0   51.27    .016       0   98.23     .12       0
   249.2    .045       0   272.9    .016       0  317.14     .12       0
Bank Sta=249.2,272.9
XS Rating Curve= 0 ,0
Exp/Cntr=0.3,0.1

Type RM Length L Ch R = 1 ,4304.5  ,187,201.7,216.8
XS GIS Cut Line= 3
     2344183.442      397492.154     2344324.067      397441.372
     2344555.513       397426.16
#Sta/Elev= 30
       0  647.24    23.6  638.14   40.43634.0815    78.7  629.73  103.87624.3514
   149.5  611.05   165.5  607.82   173.5   602.9   177.5  601.71   185.5  601.24
   197.5  597.99   205.5  597.05   220.2  598.49   233.5  601.81   241.5  602.74
   249.5  602.26   261.5  599.45   273.5  599.91   281.5  601.51  289.53605.2404
   293.5  606.62   305.5  608.11  323.46609.1549   329.5   609.2   337.5  613.52
   345.5  615.06   349.5  617.25   353.5  620.95   357.5  623.61   381.5  632.37
#Mann= 7 ,-1 , 0
       0     .12       0   40.43    .016       0  103.87     .12       0
   197.5    .045       0   220.2     .12       0  289.53    .016       0
  323.46     .12       0
Bank Sta=197.5,220.2
XS Rating Curve= 0 ,0
Exp/Cntr=0.3,0.1

Type RM Length L Ch R = 1 ,4102.8  ,210.7,213.5,215.9
XS GIS Cut Line= 2
     2344163.911      397544.237     2344528.494      397725.227
#Sta/Elev= 30
       0  651.12       4  649.34   15.47648.4046      20     648    23.9  646.65
    31.9  642.77   58.82  631.16    83.8   619.2   103.8  608.39   111.7  604.59
   115.7  603.52   135.7  602.05   147.6  600.13   155.6  598.34   167.6  593.98
   175.6  593.47   189.5  594.23   195.5  595.19   207.5  599.56   219.5  603.01
   235.4   605.8  245.66606.8938   259.4   607.8   275.4     607   279.3  608.25
  284.06610.6375   287.3  611.65   299.3  612.62   327.2  616.18     407  630.94
#Mann= 7 ,-1 , 0
       0     .12       0   15.47    .016       0   58.82     .12       0
   167.6    .045       0   189.5     .12       0  245.66    .016       0
  284.06     .12       0
Bank Sta=167.6,189.5
XS Rating Curve= 0 ,0
Exp/Cntr=0.3,0.1

Type RM Length L Ch R = 1 ,3889.3  ,211,212.6,214.2
XS GIS Cut Line= 2
     2344029.796      397688.768     2344424.328      397934.862
#Sta/Elev= 30
       0  661.32    15.9  658.79    31.8  655.66    59.6   648.5    79.5  642.67
   127.2  619.98   143.1  610.06     151  603.54     163  596.64   170.9  592.79
   174.9  591.99   178.8  591.94   194.5  592.06   198.7  592.74   214.6  596.18
   226.5   597.7   246.4  601.69   266.3   603.1   278.2  606.45   298.1     608
  307.27609.6987   321.9  610.46   337.8  609.97   341.8  611.15  345.53613.0803
   349.7  615.04   365.6  618.65   397.4  624.54   449.1  632.02     465  634.74
#Mann= 5 ,-1 , 0
       0     .12       0   170.9    .045       0   198.7     .12       0
  307.27    .016       0  345.53     .12       0
Bank Sta=170.9,198.7
XS Rating Curve= 0 ,0
Exp/Cntr=0.3,0.1

Type RM Length L Ch R = 1 ,3676.7  ,298.1,297.3,296.4
XS GIS Cut Line= 2
     2343868.338      397820.279     2344294.119      398124.966
#Sta/Elev= 30
       0   667.3   33.81 666.955      56  665.41    83.9  661.43    95.9  658.64
   123.9  649.82   159.9  629.95   183.8  614.16   199.8  602.33   207.8  597.26
   211.8  595.92   215.8  595.45   219.8  594.29   223.8  592.56   227.8  591.84
   247.8  591.36   255.8  592.54   279.8  595.93   303.8  596.42   355.7  601.12
   363.7  602.35   375.7  605.31   411.7  610.12  421.66 612.702   431.6  614.89
   455.6  615.59   459.6  616.62  462.49618.1011   467.6  620.18   523.6  632.06
#Mann= 6 ,-1 , 0
       0     .06       0   33.81     .12       0   223.8    .045       0
   255.8     .12       0  421.66    .016       0  462.49     .12       0
Bank Sta=223.8,255.8
XS Rating Curve= 0 ,0
Exp/Cntr=0.3,0.1

Type RM Length L Ch R = 1 ,3379.4  ,302,301.5,301.1
XS GIS Cut Line= 3
     2343757.661      398020.799     2343786.307      398117.154
     2344104.015      398352.831
#Sta/Elev= 30
       0  658.81    38.7  650.74    69.6  642.13    96.7  633.16   112.5   624.8
   124.5   615.9   128.5  611.88   140.5  595.14   144.5  592.25   148.5  590.81
   152.5  589.79   156.5  589.59   164.4  590.45   172.4  592.22   184.4  592.33
   192.4  591.18   204.4  587.82   212.4  587.06   224.4  587.46   229.4  588.44
   244.4  594.08   260.4  596.03   280.3  596.45  311.22599.4774   404.2  607.22
   444.2  612.54   468.1  614.63   480.1  616.78   494.3621.1835   496.1  621.71
#Mann= 5 ,-1 , 0
       0     .12       0   204.4    .045       0   229.4     .12       0
  311.22     .06       0   494.3    .016       0
Bank Sta=204.4,229.4
XS Rating Curve= 0 ,0
Exp/Cntr=0.3,0.1