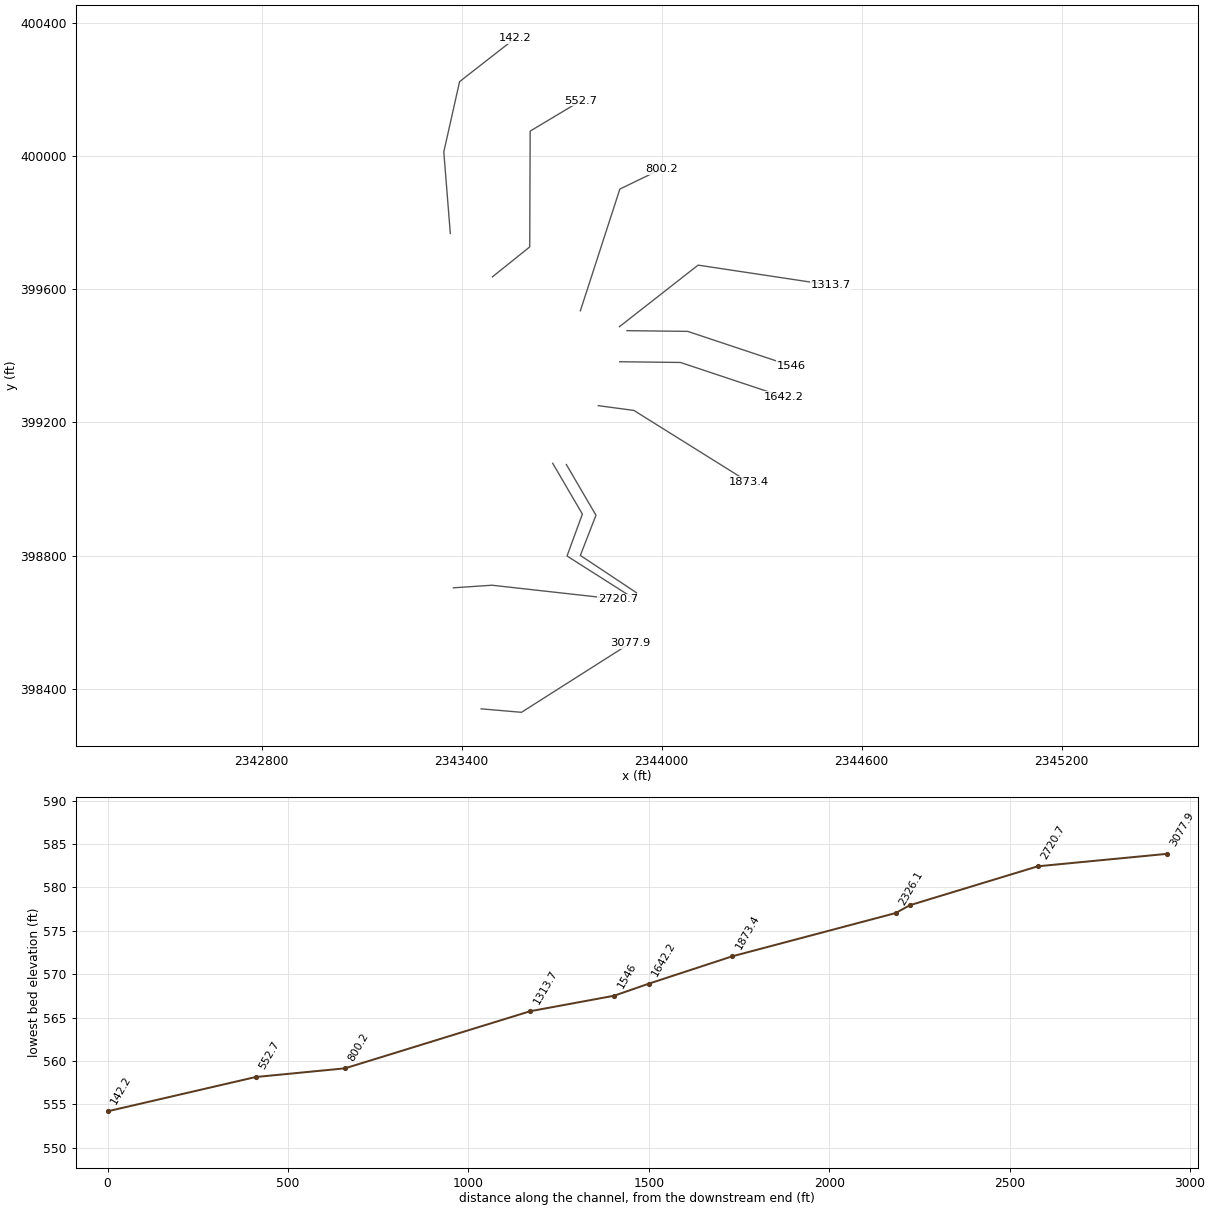
HEC-RAS study MOUNTAINRN.prj: MOUNTAINRN

--- MOUNTAINRN.g01 (geometry) --- (continued)

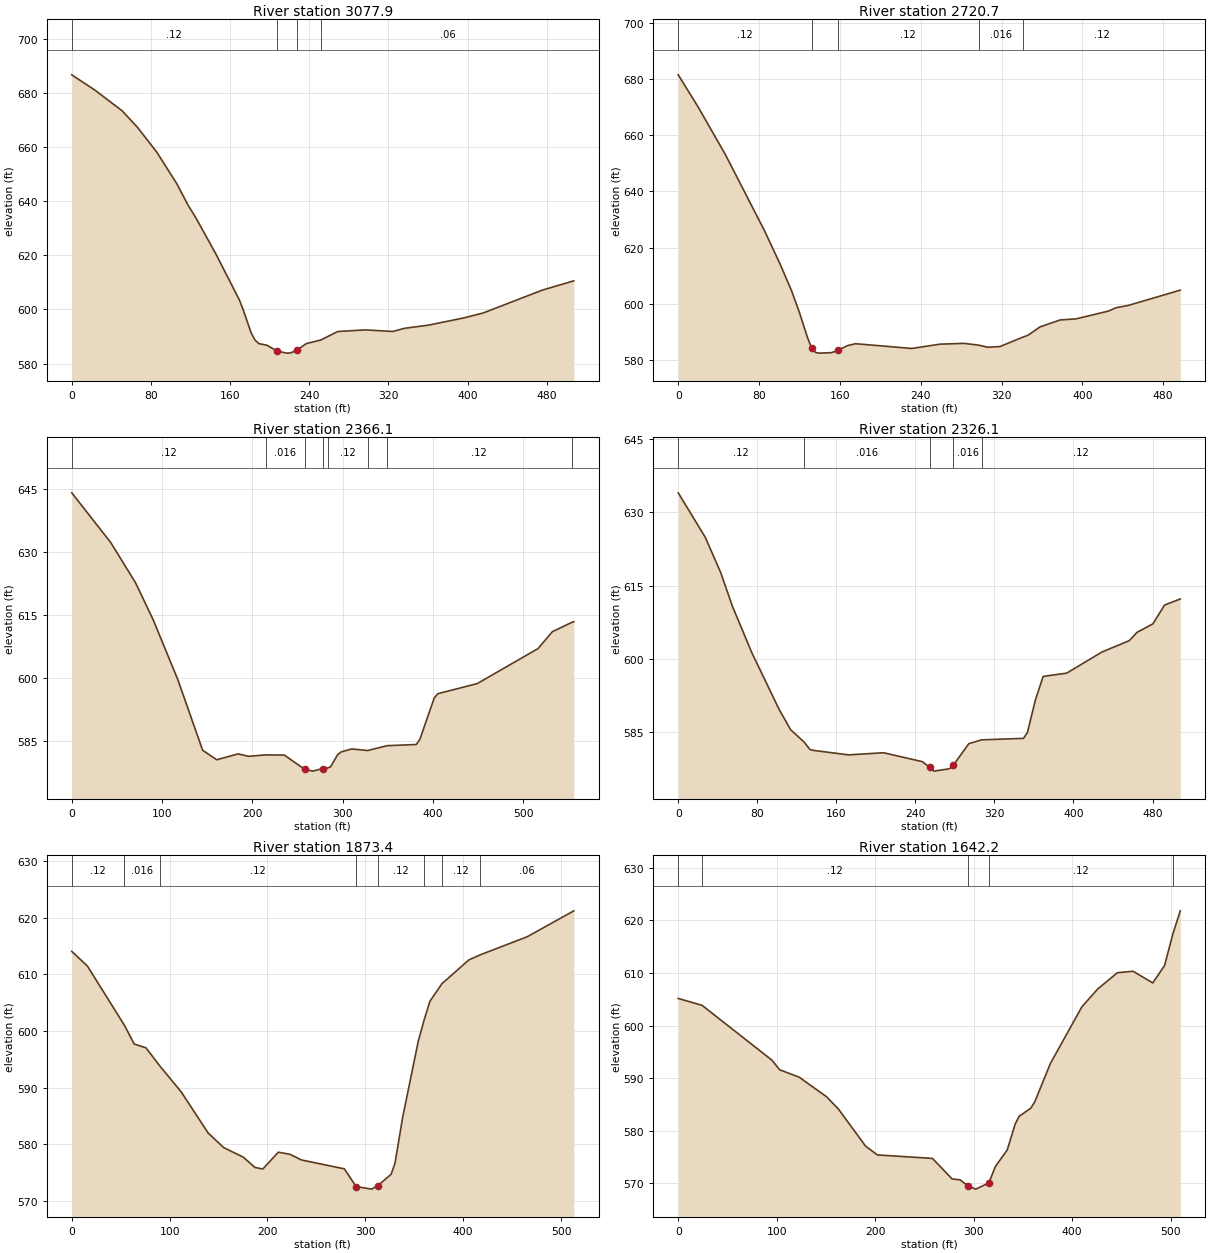
Type RM Length L Ch R = 1 ,3077.9  ,375.3,357.2,339.2
XS GIS Cut Line= 3
     2343458.182       398339.81     2343579.276      398329.393
     2343904.796      398536.424
#Sta/Elev= 30
       0  686.73    23.5  681.05      51   673.4    66.6  667.23    86.2  658.01
   105.9  646.62   117.6   638.5   125.5  633.81   145.4  620.67   169.3  603.56
   173.2  599.91   181.2  591.39   185.2  588.65   189.2  587.34   197.1   586.8
   207.1  584.68     217  583.86     221  583.93   227.1  584.88   236.9  587.36
  251.85588.7421   268.7  591.84   296.5  592.45   324.4  591.87   336.3  593.04
   360.2  594.19     396  596.86   415.8  598.71   475.5  607.16   507.3  610.59
#Mann= 4 ,-1 , 0
       0     .12       0   207.1    .045       0   227.1     .12       0
  251.85     .06       0
Bank Sta=207.1,227.1
XS Rating Curve= 0 ,0
Exp/Cntr=0.3,0.1

Type RM Length L Ch R = 1 ,2720.7  ,399.6,354.5,309.5
XS GIS Cut Line= 3
     2343374.849      398703.091     2343490.734      398710.904
     2343869.217        398668.7
#Sta/Elev= 30
       0  681.54    19.4  670.26    46.5  653.27    85.2  626.16   100.7  614.26
   112.3  604.55   120.1  596.76     128  587.94     132  584.31     136  582.65
     140  582.43   151.8   582.6   157.9   583.4   167.7  585.12   175.6  585.78
   231.2  584.09     259  585.62   282.8  585.91  297.69585.2567   306.6  584.51
   318.5  584.78  340.96588.0858   346.2  588.79   358.1  591.76     378  594.24
   393.8  594.63   425.6  597.38   433.5   598.6   445.4  599.41     497  604.86
#Mann= 5 ,-1 , 0
       0     .12       0     132    .045       0   157.9     .12       0
  297.69    .016       0  340.96     .12       0
Bank Sta=132,157.9
XS Rating Curve= 0 ,0
Exp/Cntr=0.3,0.1

Type RM Length L Ch R = 1 ,2366.1  ,46.7,40,37.8
XS GIS Cut Line= 4
     2343673.026      399076.789      2343761.98      398924.485
     2343715.973      398798.617     2343923.438      398666.673
#Sta/Elev= 30
       0  643.98    43.1  632.21    70.6  622.67    90.2  613.87   117.6  599.61
     145   582.9   160.7  580.65   184.3  582.04   196.1  581.46  214.74581.8026
   235.5  581.76   258.2  578.36     267  577.95   278.2  578.57  283.39578.6939
   286.7  578.94   294.6  581.86   298.6  582.52   310.4  583.21   327.9582.8343
  349.31583.9859   381.8  584.27   385.7  585.49   401.6  595.31   405.6  596.32
   449.2  598.71   516.6  607.02   532.5  611.03  553.86613.2248   556.3  613.42
#Mann= 8 ,-1 , 0
       0     .12       0  214.74    .016       0   258.2    .045       0
   278.2     .06       0  283.39     .12       0   327.9    .016       0
  349.31     .12       0  553.86     .06       0
Bank Sta=258.2,278.2
XS Rating Curve= 0 ,0
Exp/Cntr=0.3,0.1

Type RM Length L Ch R = 1 ,2326.1  ,411.1,452.7,490
XS GIS Cut Line= 4
     2343713.824      399073.317     2343802.778      398921.013
     2343755.903      398800.353     2343924.306      398688.374
#Sta/Elev= 30
       0  633.96    27.4  624.85    43.1  617.59    54.9  610.72    74.5  601.26
   101.9  589.75   113.7  585.52  127.58 582.953   133.3  581.46   137.2  581.27
   172.5  580.36   207.8   580.8     247  578.98   254.8  577.79   258.8  577.04
   274.4  577.52   278.4  578.25   294.1  582.66  307.22583.4417   349.4  583.74
   353.4  584.94   361.3   591.5   369.3  596.41   393.1  597.08   428.8   601.4
   456.5  603.73   464.4  605.44   480.3  607.15   492.2  611.01   508.1  612.26
#Mann= 5 ,-1 , 0
       0     .12       0  127.58    .016       0   254.8    .045       0
   278.4    .016       0  307.22     .12       0
Bank Sta=254.8,278.4
XS Rating Curve= 0 ,0
Exp/Cntr=0.3,0.1

Type RM Length L Ch R = 1 ,1873.4  ,225.7,231.2,236.8
XS GIS Cut Line= 3
     2343809.744      399249.966     2343916.515      399235.643
     2344260.265      399020.799
#Sta/Elev= 30
       0  614.03      16  611.44   53.79600.9888    63.8  597.68    75.8  597.01
   90.32593.7326   111.7  589.26   139.5  581.94   155.4  579.38   175.3   577.7
   187.2  575.89   195.2  575.61   211.1  578.58     223  578.21   234.9   577.2
   278.6  575.64   290.5  572.52   306.4  572.06   312.7  572.67   326.3  574.67
   330.3   576.6   338.2  584.78   354.1  598.17  360.33602.0576     366  605.22
  378.37608.3364   405.8  612.52  417.68613.4387   465.4  616.61   513.1  621.19
#Mann= 8 ,-1 , 0
       0     .12       0   53.79    .016       0   90.32     .12       0
   290.5    .045       0   312.7     .12       0  360.33     .06       0
  378.37     .12       0  417.68     .06       0
Bank Sta=290.5,312.7
XS Rating Curve= 0 ,0
Exp/Cntr=0.3,0.1

Type RM Length L Ch R = 1 ,1642.2  ,96.1,96.2,96.1
XS GIS Cut Line= 3
     2343873.991      399381.807     2344056.283      399379.637
     2344367.036      399276.008
#Sta/Elev= 30
       0  605.17   24.25603.8558    95.1  593.44     103  591.61   122.9  590.19
   150.6  586.48   162.5  584.18   190.3  577.08   202.3  575.41   258.2  574.75
   278.2  570.84   286.2  570.68   294.2  569.52   302.2  568.91   315.5  570.09
   322.1  573.22   334.1  576.35   342.1  581.23   346.1  582.73   358.1  584.31
   362.1  585.52     378  592.82     410  603.59     426  606.96     446  610.06
   461.9  610.34   481.9  608.12   493.9  611.42  502.39617.4634   509.9  621.83
#Mann= 5 ,-1 , 0
       0    .016       0   24.25     .12       0   294.2    .045       0
   315.5     .12       0  502.39    .016       0
Bank Sta=294.2,315.5
XS Rating Curve= 0 ,0
Exp/Cntr=0.3,0.1

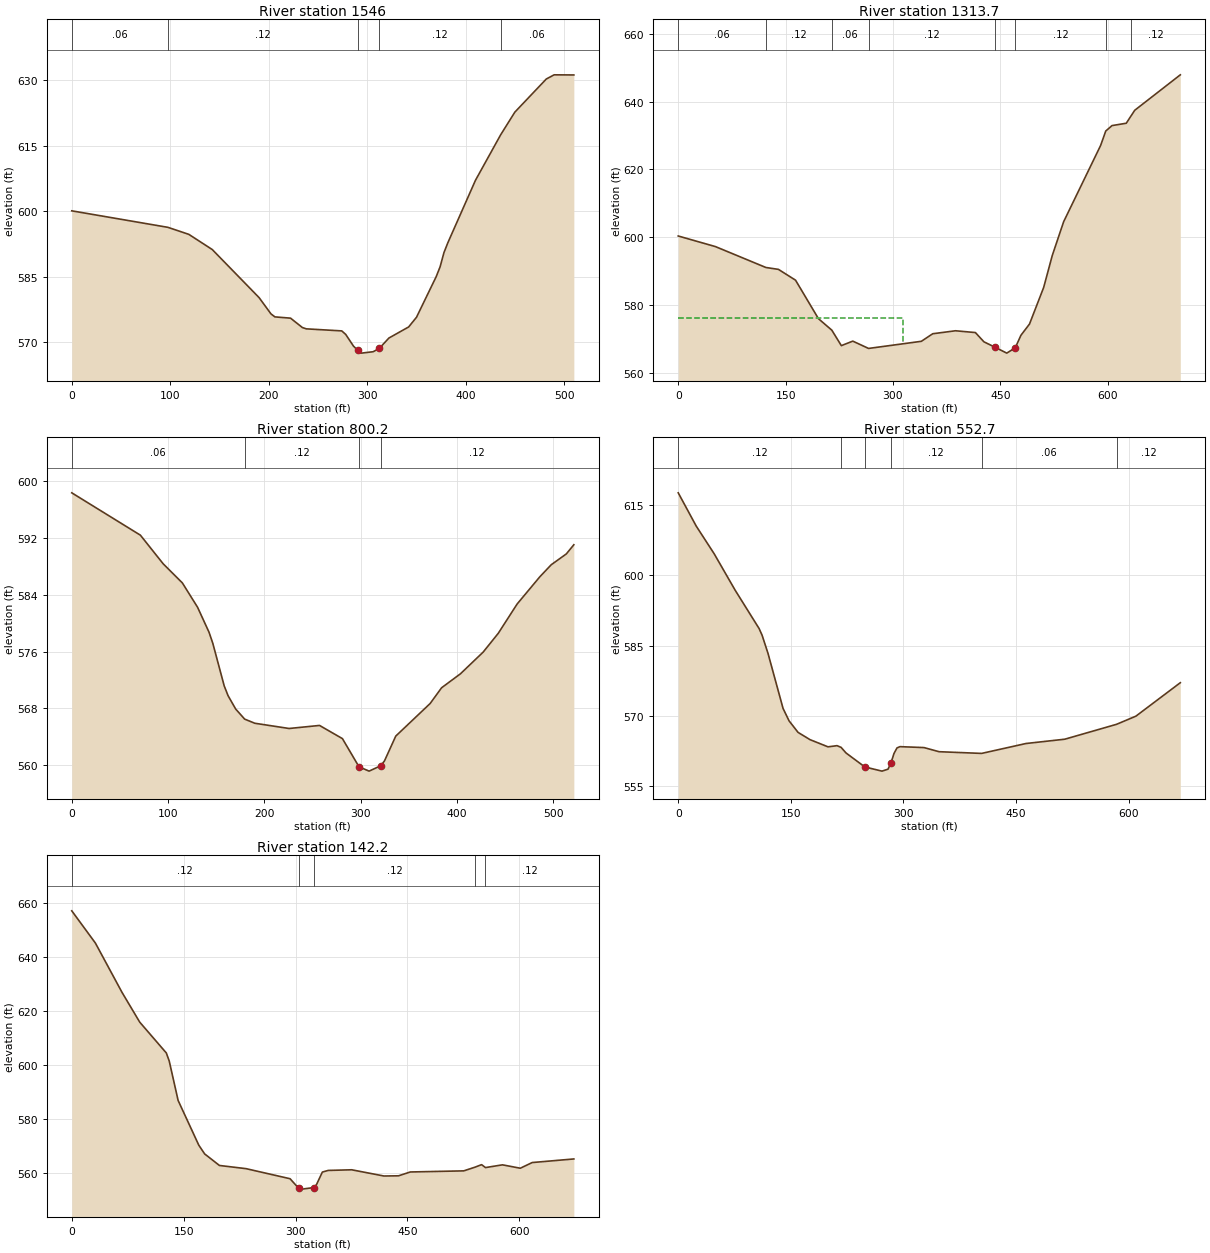
Type RM Length L Ch R = 1 ,1546    ,228.2,232.4,236.7
XS GIS Cut Line= 3
     2343895.693      399475.123     2344077.984      399472.953
     2344388.737      399369.324
#Sta/Elev= 30
       0  600.11   97.69596.3282   118.9  594.72   142.7  591.24   190.3  580.22
   202.3  576.51   206.3  575.82   222.2  575.53   234.2  573.38   238.2  573.08
   274.2  572.61   278.2  571.81   286.2   569.1   290.2  568.24   294.2  567.52
   306.1  567.84   312.3   568.6   322.1  570.98   342.1  573.51   350.1  575.73
   370.1  585.03   374.1  587.31     378  590.55     382  592.83     410  607.11
  435.63617.5464     450  622.72   481.9   630.3   489.9  631.26   509.9  631.23
#Mann= 5 ,-1 , 0
       0     .06       0   97.69     .12       0   290.2    .045       0
   312.3     .12       0  435.63     .06       0
Bank Sta=290.2,312.3
XS Rating Curve= 0 ,0
Exp/Cntr=0.3,0.1

Type RM Length L Ch R = 1 ,1313.7  ,477.7,513.5,549.2
XS GIS Cut Line= 3
     2343873.112      399486.945     2344109.224      399671.841
     2344506.359      399611.945
#Sta/Elev= 30
       0  600.31      52  597.18  122.44591.0187     140  590.46   163.9  587.27
   195.9  575.91  214.59572.5184   227.9  567.95   243.9  569.28  265.94567.1224
   339.7  569.23   355.6  571.46   387.4  572.34   415.2  571.81   427.1  569.08
     443  567.44     459  565.74   470.9  567.32   478.8     571   490.8  574.33
   510.6  585.13   522.6  594.55   538.5  604.53   590.2  627.05  597.33631.2916
   606.1   632.9     626  633.59  631.93635.5223   637.9  637.43   701.5  647.88
#Mann= 8 ,-1 , 0
       0     .06       0  122.44     .12       0  214.59     .06       0
  265.94     .12       0     443    .045       0   470.9     .12       0
  597.33    .016       0  631.93     .12       0
#XS Ineff= 2 , 0
          314.25   576.2
Permanent Ineff=
       F       F
Bank Sta=443,470.9
XS Rating Curve= 0 ,0
Exp/Cntr=0.3,0.1

Type RM Length L Ch R = 1 ,800.2   ,239.4,247.5,255.1
XS GIS Cut Line= 3
     2343755.925      399534.688     2343874.415       399900.14
     2343998.112      399960.036
#Sta/Elev= 30
       0  598.39    71.3  592.42      95  588.38   114.9  585.69   130.7  582.26
   142.6  578.74   146.5  577.19   158.4  571.16   162.4  569.79   170.3  567.91
  179.59566.4949   190.1  565.91   225.8  565.17   257.4   565.6   281.2  563.74
   298.4  559.77   308.9  559.16   320.8  559.91   324.8  560.58   336.6   564.1
   372.3  568.69   384.2  570.91   403.8  572.88   427.4  575.94   443.1  578.59
   462.7  582.72   486.3  586.56   498.1  588.25   513.8  589.78   521.6  591.07
#Mann= 4 ,-1 , 0
       0     .06       0  179.59     .12       0   298.4    .045       0
   320.8     .12       0
Bank Sta=298.4,320.8
XS Rating Curve= 0 ,0
Exp/Cntr=0.3,0.1

Type RM Length L Ch R = 1 ,552.7   ,415.6,410.5,405.4
XS GIS Cut Line= 4
     2343492.036      399636.685     2343604.015      399726.529
     2343605.317      400074.185     2343757.661      400165.331
#Sta/Elev= 30
       0  617.62    23.9  610.53    47.9  604.59    75.8  596.82   107.7  588.63
   111.7   587.2   119.6  583.31   139.6  571.57   147.6  568.91   159.6  566.44
   175.5  564.89   199.5  563.35   211.5   563.6  216.93563.2376   223.5  562.04
   248.6  559.05   271.4  558.16   279.4  558.57   283.4  559.91   287.4  561.93
   291.4  563.12   295.4  563.39   327.4  563.19   347.4  562.31  404.12561.9443
   463.2  564.06   514.9  564.98  583.88568.1609   609.6   569.9   668.8  577.05
#Mann= 6 ,-1 , 0
       0     .12       0  216.93     .06       0   248.6    .045       0
   283.4     .12       0  404.12     .06       0  583.88     .12       0
Bank Sta=248.6,283.4
XS Rating Curve= 0 ,0
Exp/Cntr=0.3,0.1

Type RM Length L Ch R = 1 ,142.2   ,128.9,142.2,155.4
XS GIS Cut Line= 4
     2343365.734      399766.893     2343346.203      400011.685
     2343393.512      400222.622     2343560.178      400352.831
#Sta/Elev= 30
       0  657.24    31.7   645.3    67.3  627.09    91.1  616.04   126.8  604.61
   130.7  601.61   142.6  587.04   170.3  570.49   178.2  567.24     198  562.97
   233.7  561.79   292.7  558.06   304.3  554.51   308.5  554.21   324.3  554.77
   328.1  555.87     336  560.52   343.8  561.13   375.3  561.37   418.5  559.07
   438.2  559.14   453.9  560.56   525.6  560.97  540.95562.3646   549.5  563.27
  554.74562.1878   577.5   563.2   601.4  561.95   617.4  564.05   673.2  565.38
#Mann= 5 ,-1 , 0
       0     .12       0   304.3    .045       0   324.3     .12       0
  540.95     .06       0  554.74     .12       0
Bank Sta=304.3,324.3
XS Rating Curve= 0 ,0
Exp/Cntr=0.3,0.1

Chan Stop Cuts=-1
Use User Specified Reach Order=0
Composite Channel Slope=5